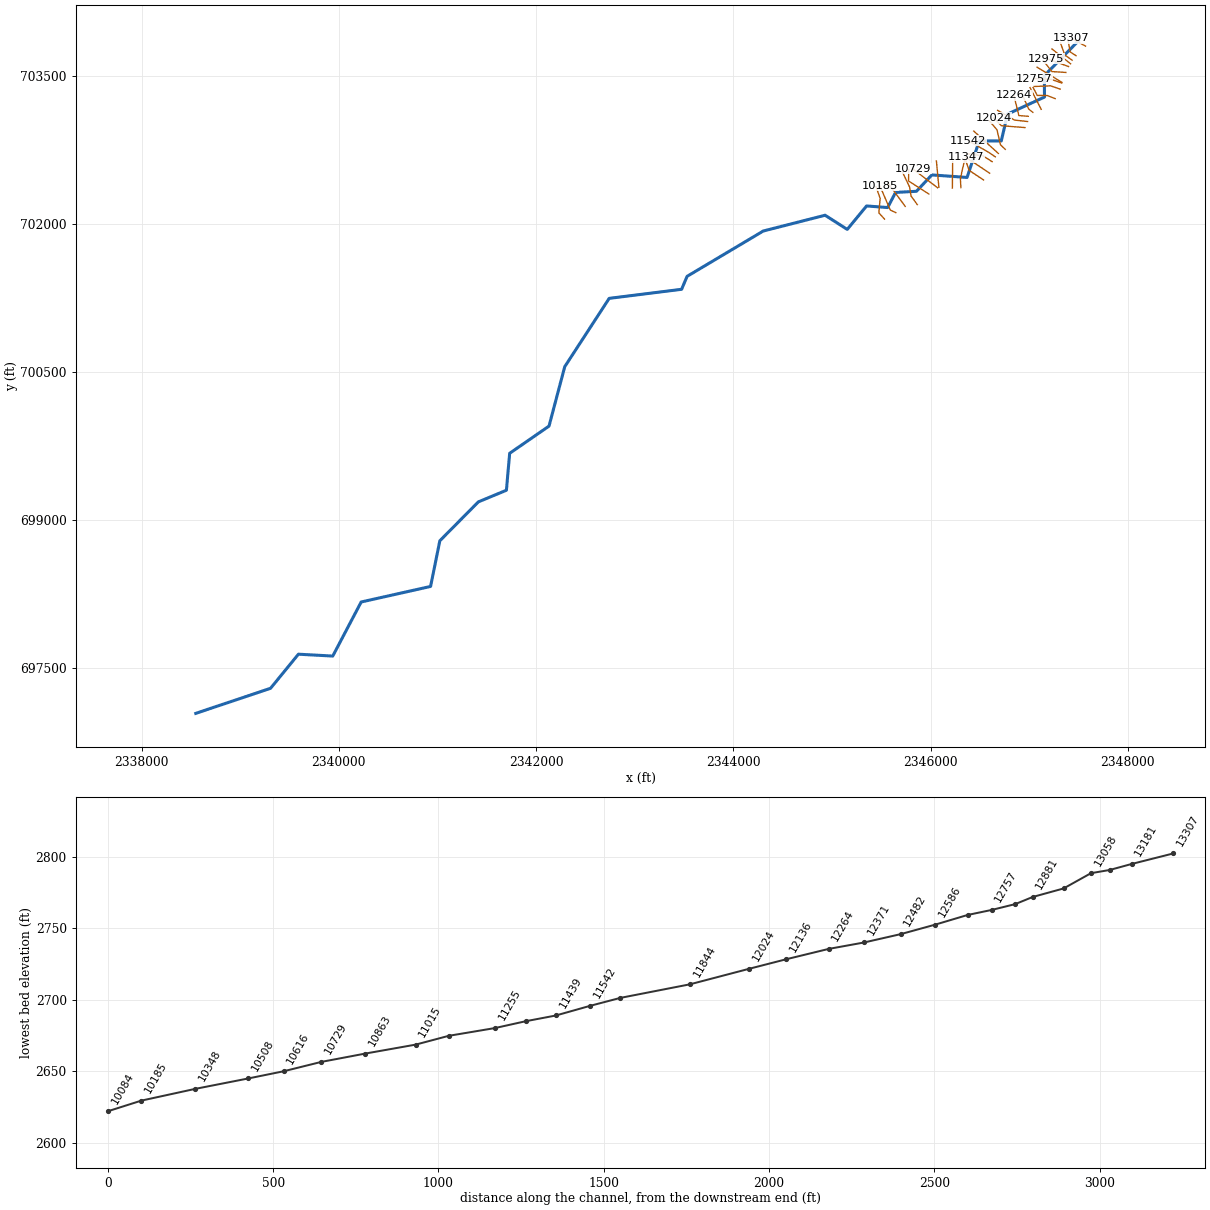
--- TAYLORRN.prj (project) ---

Proj Title=TAYLORRN
Current Plan=p01
Default Exp/Contr=0,0
English Units
Geom File=g01
Flow File=f01
Plan File=p01
BEGIN DESCRIPTION:
----------MODEL BY WOOD PLC 2022----------
AFH study
Randolph County, WV
HEC-RAS Version: RAS 6.2
Vertical Datum: NAVD88
Projection: NAD 1983 StatePlane West Virginia S FIPS 4702 (US Feet)
Terrain: 1-meter LIDAR (FEMA Region III 3DEP collected 2016-2018)
Land Use: 2019 NLCD
Hydrologic Method:
WV SIR2010-5033 regression equations
Additional Model Notes:
None
END DESCRIPTION:
DSS Export Rating Curves= 0
DSS Export Rating Curve Sorted= 0
DSS Export Volume Flow Curves= 0
DXF OffsetX= 0
DXF OffsetY= 0
DXF ScaleX= 0
DXF ScaleY= 0

--- TAYLORRN.p01 (plan) ---

Plan Title=Floodplain
Program Version=6.20
Short Identifier=Floodplain
Geom File=g01
Flow File=f01
Subcritical Flow
K Sum by GR= 0
Std Step Tol= 0.01
Critical Tol= 0.01
Num of Std Step Trials= 20
Max Error Tol= 0.3
Flow Tol Ratio= 0.001
Split Flow NTrial= 30
Split Flow Tol= 0.02
Split Flow Ratio= 0.02
Log Output Level= 0
Friction Slope Method= 1
Unsteady Friction Slope Method= 2
Unsteady Bridges Friction Slope Method= 1
Parabolic Critical Depth
Global Vel Dist= 0 , 0 , 0
Global Log Level= 0
CheckData=True
Encroach Param=-1 ,0,0, 0
Mapping Interval=1HOUR
Computation Time Step Use Courant=        0
Computation Time Step Use Time Series=    0
Computation Time Step Count To Double=0
Computation Time Step Max Doubling=0
Computation Time Step Max Halving=0
Computation Time Step Residence Courant=0
Run HTab= 0
Run UNet= 0
Run Sediment= 0
Run PostProcess= 0
Run WQNet= 0
Run RASMapper=-1
UNET Theta= 0
UNET Theta Warmup= 0
UNET ZTol= 0
UNET ZSATol= 0
UNET MxIter= 0
UNET Max Iter WO Improvement= 0
UNET MaxInSteps= 0
UNET DtIC= 0
UNET DtMin= 0
UNET MaxCRTS= 0
UNET WFStab= 0
UNET SFStab= 0
UNET WFX= 1
UNET SFX= 1
UNET Gravity=32.174
UNET 1D Methodology=Finite Difference
UNET DSS MLevel= 1
UNET Pardiso=0
UNET DZMax Abort= 0
UNET Use Existing IB Tables= 0
UNET Froude Reduction=False
UNET Froude Limit= 0
UNET Froude Power= 0
UNET D1 Cores= 0
UNET WindReference=Eulerian
UNET WindDragFormulation=Hsu (1988)
UNET D2 Coriolis=0
UNET D2 Cores= 0
UNET D2 Theta= 1
UNET D2 Theta Warmup= 1
UNET D2 Z Tol= 0.01
UNET D2 Volume Tol= 0.01
UNET D2 Max Iterations= 20
UNET D2 Equation= 0
UNET D2 RampUpFraction=0.1
UNET D2 TimeSlices= 1
UNET D2 Turbulence Formulation=Non-Conservative (original)
UNET D2 Eddy Viscosity=0.3
UNET D2 Transverse Eddy Viscosity=0.1
UNET D2 Smagorinsky Mixing=0
UNET D2 BCVolumeCheck=0
UNET D2 Cores=0
UNET D2 SolverType=PARDISO (Direct)
UNET D2 Minimum Iterations= 2147483647
UNET D2 Maximum Iterations= 2147483647
UNET D2 Restart Number= 10
UNET D2 Relaxation Coeff=1.3
UNET D2 SOR Precondition Iterations= 10
UNET D2 ILUT Maximum Fill= 8
UNET D2 ILUT Tolerance=1E-08
UNET D1D2 MaxIter= 0
UNET D1D2 ZTol=0.01
UNET D1D2 QTol=0.1
UNET D1D2 MinQTol=1
Write IC File= 0
Write IC File at Fixed DateTime=0
Write IC File at Sim End=0
Echo Input=False
Echo Parameters=False
Echo Output=False
Write Detailed= 0
HDF Write Warmup=0
HDF Write Time Slices=0
HDF Flush=0
HDF Compression= 1
HDF Chunk Size= 1
HDF Spatial Parts= 1
HDF Use Max Rows=0
HDF Fixed Rows= 1
Calibration Method= 0
Calibration Iterations= 20
Calibration Max Change=0.05
Calibration Tolerance=0.2
Calibration Maximum=1.5
Calibration Minimum=0.5
Calibration Optimization Method= 1
WQ AD Non Conservative
WQ ULTIMATE=-1
WQ Max Comp Step=1HOUR
WQ Output Interval=15MIN
WQ Output Selected Increments= 0
WQ Output face flow=0
WQ Output face velocity=0
WQ Output face area=0
WQ Output face dispersion=0
WQ Output cell volume=0
WQ Output cell surface area=0
WQ Output cell continuity=0
WQ Output cumulative cell continuity=0
WQ Output face conc=0
WQ Output face dconc_dx=0
WQ Output face courant=0
WQ Output face peclet=0
WQ Output face adv mass=0
WQ Output face disp mass=0
WQ Output cell mass=0
WQ Output cell source sink temp=0
WQ Output nsm pathways=0
WQ Output nsm derived pathways=0
WQ Create Restart=0
WQ Fixed Restart=0
WQ System Summary=0
WQ Write To DSS=0
Sorting and Armoring Iterations= 10
XS Update Threshold= 0.02
Bed Roughness Predictor= 0
Hydraulics Update Threshold= 0.02
Energy Slope Method= 1
Volume Change Method= 1
Sediment Retention Method= 0
Sediment TS Multiplier= 1
Warm Up Method= 0
XS Weighting Method= 0
Number of US Weighted Cross Sections= 1
Number of DS Weighted Cross Sections= 1
Upstream XS Weight=0
Main XS Weight=1
Downstream XS Weight=0
Number of DS XS's Weighted with US Boundary= 1
Upstream Boundary Weight= 1
Weight of XSs Associated with US Boundary= 0
Number of US XS's Weighted with DS Boundary= 1
Downstream Boundary Weight= 0.5
Weight of XSs Associated with DS Boundary= 0.5
Percentile Method= 0
Sediment Output Level= 3
Mass or Volume Output= 0
Output Increment Type= 1
Profile and TS Output Increment= 1
Transport Output Increment 1
XS Output Flag= 0
XS Output Increment= 10
Read HDF5 Sediment Hotstart= 0
Sediment Hotstart Type= 0
Write Gradation File= 0
Read Gradation Hotstart= 0
Write HDF5 File= 1
Write Binary Output= 1
Write DSS Sediment File= 0
DSS Sediment Output Type= 1
SV Curve= 0
Specific Gage Flag= 0
Subcell Erosion Methods= 0
Subcell Deposition Methods= 0
Advection Scheme= 1
Matrix Solver= 0
Implicit Weighting Factor= 1
Maximum Outer Loop Convergence Iterations= 5
Convergence Maximum Absolute= 0.001
Convergence RMSE= 0.0001
Grain Fractions Max Abs Error= 0.001
Max Subgrid Regions= 1
Max Subgrid Length Scale= 3.402823E+38
Initial Layer Thickness= 3.402823E+38
Min Layer Thickness= 3.402823E+38
Max Layer Thickness= 3.402823E+38
Number of Layers= 5

--- TAYLORRN.f01 (steady flow) ---

Flow Title=Flow
Program Version=6.20
Number of Profiles= 1
Profile Names=P100yr
River Rch & RM=TAYLORRN,Main,13307
     370
River Rch & RM=TAYLORRN,Main,10616
     417
River Rch & RM=TAYLORRN,Main,9017
     475
River Rch & RM=TAYLORRN,Main,6316
     670
River Rch & RM=TAYLORRN,Main,6104
     760
River Rch & RM=TAYLORRN,Main,2900
     893
Boundary for River Rch & Prof#=TAYLORRN,Main            , 1
Up Type= 0
Dn Type= 3
Dn Slope=0.0242
DSS Import GetInterval= 0
DSS Import GetPeak= 0
DSS Import FillOption= 0

--- TAYLORRN.g01 (geometry) ---

Geom Title=Geometry
Program Version=6.20

River Reach=TAYLORRN        ,Main
Reach XY= 30
2347499.92844284703861.5148524052347153.24200001703507.313999996
     2347154.978703290.734000012     2346780.412703117.557000011
2346716.61000003702844.9880000052346493.08500002702845.422000021
2346369.82099998702474.762000009     2346012.617702500.370000005
     2345856.367702334.1369999952345644.99500002702322.851999998
       2345564.7702169.2060000152345351.06402281702185.556908876
2345154.97800003 701947.505000012344930.49800001702091.254999995
2344303.45000003701931.1850000022343531.05400002701471.212000012
2343475.23800002701339.7880000032342741.07196668701247.713029992
 2342290.4446823700554.5227152852342130.84000002699951.441000015
2341731.79217969699675.465535775     2341698.904699300.787000015
2341414.27400003699182.439999998     2341023.809698787.904000014
2340929.95999999698324.4640000162340226.24300003698166.774000019
2339938.05800003 697617.990000012339589.78400002697636.917999998
2339307.34200001697290.929000005      2338548.83697036.441000015

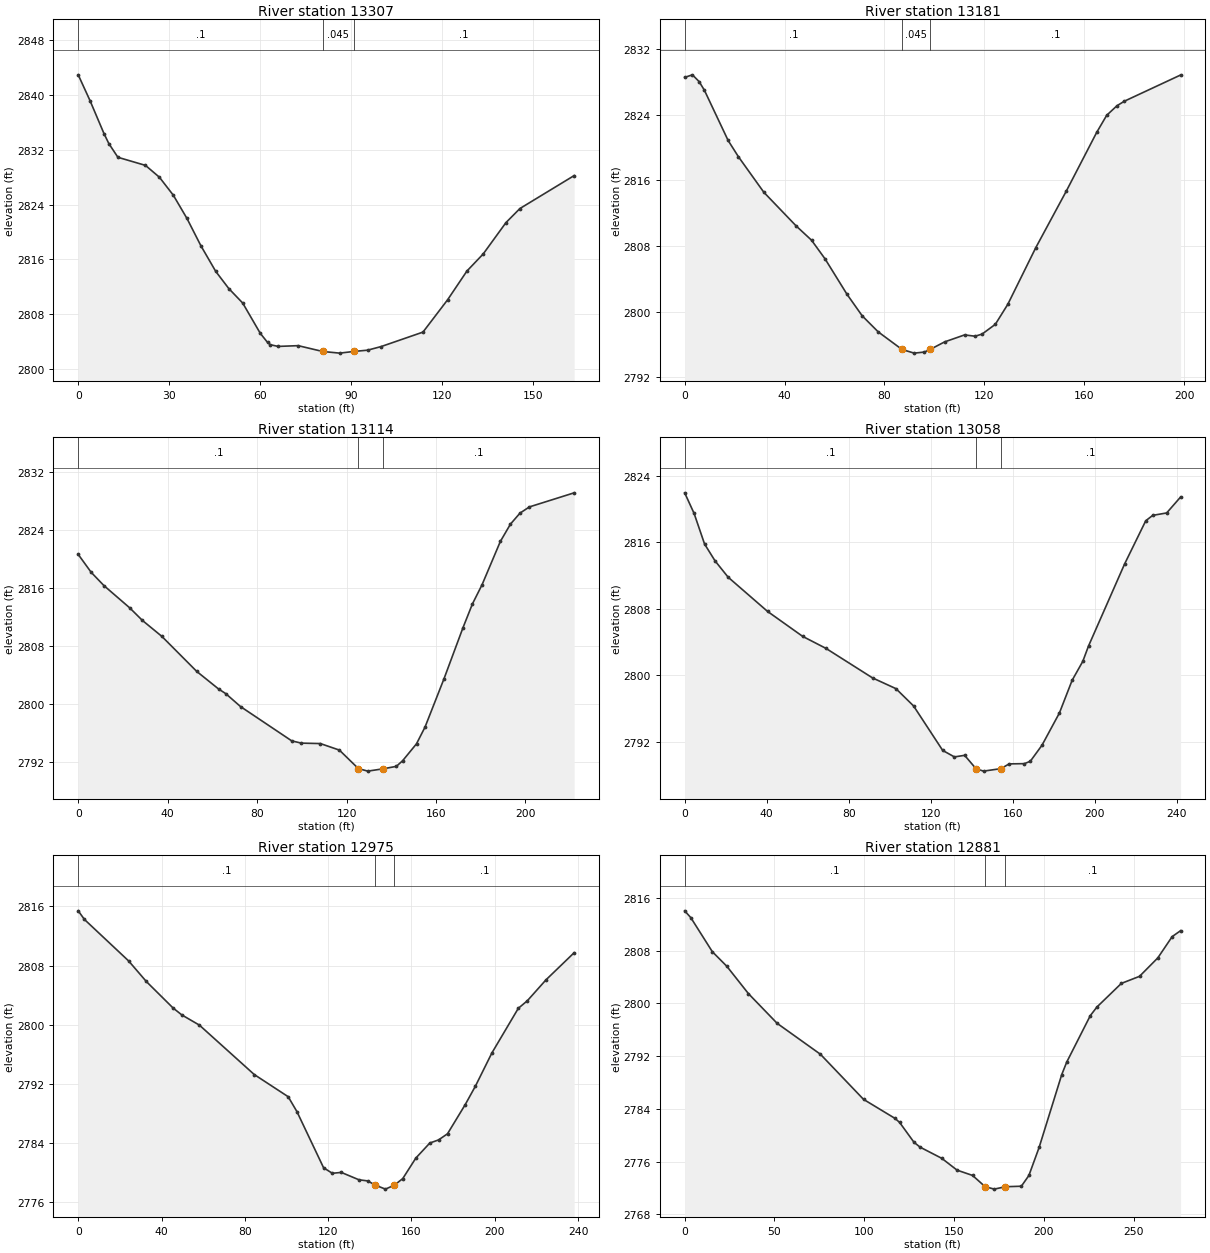
Type RM Length L Ch R = 1 ,13307   ,131.2,126.4,122.5
XS GIS Cut Line= 2
 2347571.5824182703806.7978819242347428.55410769703886.396246033
#Sta/Elev= 30
       0 2842.95     3.9 2839.18     8.5 2834.38    10.1 2832.92    13.1 2830.91
    22.2 2829.73    26.8    2828    31.4 2825.37    35.9 2821.98    40.5 2817.99
    45.4 2814.25    49.7 2811.75    54.3 2809.63    60.1 2805.21    62.5 2803.88
    63.4 2803.55      66  2803.3    72.6 2803.41    80.7 2802.56    86.3 2802.32
    90.9 2802.56    95.5 2802.75     100 2803.28   113.8 2805.39   121.9 2810.09
   128.3  2814.3   133.7 2816.81   141.2 2821.38   145.8 2823.43   163.7 2828.24
#Mann= 3 ,-1,0
       0      .1       0    80.7    .045       0    90.9      .1       0
Bank Sta=80.7,90.9
XS Rating Curve= 0 ,0
Exp/Cntr(USF)=0,0
Exp/Cntr=0.3,0.1

Type RM Length L Ch R = 1 ,13181   ,64.8,66.2,66.8
XS GIS Cut Line= 3
 2347474.7861816 703710.042520772347415.10886426703748.657255514
2347393.34419559703874.330664952
#Sta/Elev= 30
       0 2828.53     3.1 2828.84     5.8 2828.01     7.9 2826.96    17.4 2820.84
    21.5 2818.87    31.7 2814.53    44.7 2810.41    50.8 2808.69    56.2 2806.42
      65  2802.1    71.1 2799.47    77.5 2797.52   87.032795.376    91.9 2794.93
      96 2795.06    98.3 2795.38   104.1  2796.3   112.1 2797.15   116.3 2796.99
   119.1 2797.25   124.4 2798.44   129.4 2800.88   140.6 2807.78   152.8 2814.66
     165 2821.83     169 2823.91   173.1 2825.07   176.1 2825.63   198.6 2828.82
#Mann= 3 ,-1,0
       0      .1       0   87.03    .045       0    98.3      .1       0
Bank Sta=87.03,98.3
XS Rating Curve= 0 ,0
Exp/Cntr(USF)=0,0
Exp/Cntr=0.3,0.1

Type RM Length L Ch R = 1 ,13114   ,52.9,56.9,59.3
XS GIS Cut Line= 3
2347435.46936077703664.4069251642347361.04823562703717.063381633
2347316.81681219703839.928446726
#Sta/Elev= 30
       0 2820.62     5.8 2818.15    11.5 2816.32      23 2813.26    28.7 2811.52
    37.4 2809.32      53 2804.49    62.8 2802.06      66 2801.42    72.6 2799.64
    95.5 2794.91    99.8  2794.6   108.3 2794.54   116.8 2793.64   125.3 2791.09
   129.5 2790.74   136.4 2791.06   142.3  2791.4   145.1 2792.18   151.3 2794.51
   155.1 2796.81   163.6 2803.48   172.1 2810.53   176.3 2813.79   180.6 2816.43
   188.8 2822.41   193.3 2824.79   197.6 2826.32   201.8 2827.17   221.8 2829.11
#Mann= 3 ,-1,0
       0      .1       0   125.3    .045       0   136.4      .1       0
Bank Sta=125.3,136.4
XS Rating Curve= 0 ,0
Exp/Cntr(USF)=0,0
Exp/Cntr=0.3,0.1

Type RM Length L Ch R = 1 ,13058   ,81.4,82.9,84.7
XS GIS Cut Line= 2
2347419.75327902703627.9649072652347230.89212182703778.913415808
#Sta/Elev= 30
       0 2821.95     4.6 2819.47     9.7 2815.79    14.8 2813.77    21.2  2811.8
    40.4 2807.69    57.5 2804.69    68.9 2803.24    91.6 2799.69     103  2798.4
   111.6 2796.32   125.8 2790.97   131.5 2790.19   136.5 2790.38  142.04 2788.77
   145.7 2788.48   154.2 2788.78   158.2 2789.35   165.6 2789.38   168.5 2789.66
   174.2 2791.59   182.7 2795.47   188.9  2799.4   194.1 2801.68   196.9 2803.53
   214.5  2813.4   224.8 2818.59   228.2 2819.24     235 2819.53   241.8 2821.45
#Mann= 3 ,0,0
       0      .1       0  142.04    .045       0   154.2      .1       0
Bank Sta=142.04,154.2
XS Rating Curve= 0 ,0
Exp/Cntr(USF)=0,0
Exp/Cntr=0.3,0.1

Type RM Length L Ch R = 1 ,12975   ,96.3,93.5,90.4
XS GIS Cut Line= 2
2347398.96088428703600.5170913162347174.99542277703681.256991234
#Sta/Elev= 30
       0  2815.4       3 2814.23    24.2 2808.63    32.7 2805.85    45.5 2802.28
    49.7 2801.34    58.2 2799.95    84.5 2793.28   100.8 2790.28     105 2788.27
   117.8 2780.68     122 2779.93   126.3 2780.05   134.8 2779.05     139  2778.9
  142.532778.344   147.5 2777.79   151.8 2778.33   155.8 2779.21   162.1 2781.99
   168.8 2784.02     173 2784.44   177.3 2785.27   185.8 2789.21   190.7 2791.71
   198.6 2796.19   211.3 2802.23   215.6 2803.24   224.6 2806.08   238.1 2809.74
#Mann= 3 ,-1,0
       0      .1       0  142.53    .045       0   151.8      .1       0
Bank Sta=142.53,151.8
XS Rating Curve= 0 ,0
Exp/Cntr(USF)=0,0
Exp/Cntr=0.3,0.1

Type RM Length L Ch R = 1 ,12881   ,50.3,52.8,55
XS GIS Cut Line= 3
2347371.57952692703540.137687899 2347229.7581375 703549.26480702
 2347147.6140654703655.279806043
#Sta/Elev= 30
       0 2814.05     3.4 2813.02    15.4 2807.85    23.5 2805.63    35.5 2801.49
    51.5 2796.98    75.6 2792.29    99.6 2785.45   117.2 2782.55   119.7 2781.95
   127.7 2778.94   131.1  2778.2   143.2  2776.5   151.7 2774.71   160.3 2773.91
   167.3 2772.21   172.4 2771.83  178.642772.195   187.5 2772.27   191.7  2773.9
   197.4 2778.16     210 2789.21   212.8 2791.12   225.9 2798.15   229.6 2799.46
   243.2 2803.04   253.3 2804.11   263.5 2806.91   271.5 2810.14   276.2 2811.04
#Mann= 3 ,-1,0
       0      .1       0   167.3    .045       0  178.64      .1       0
Bank Sta=167.3,178.64
XS Rating Curve= 0 ,0
Exp/Cntr(USF)=0,0
Exp/Cntr=0.3,0.1

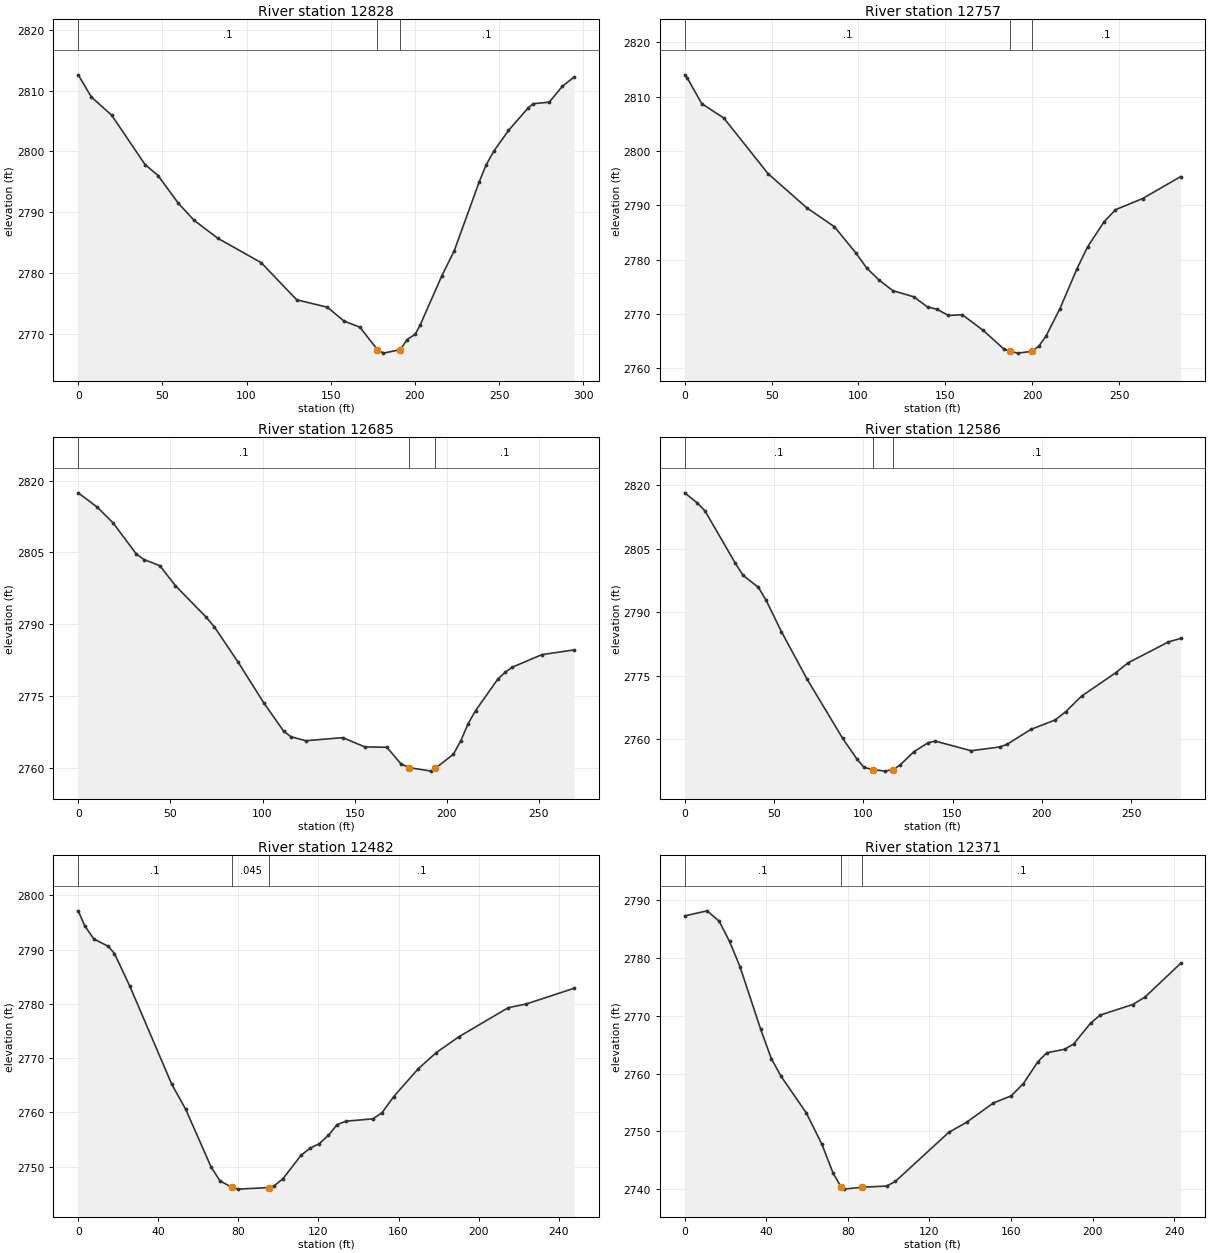
Type RM Length L Ch R = 1 ,12828   ,67.8,71,74.2
XS GIS Cut Line= 2
2347330.85853391703440.4414636512347079.51171504 703594.19831654
#Sta/Elev= 30
       0 2812.58     7.8 2808.94    19.9 2805.94    39.7 2797.83    47.4 2796.03
    59.4  2791.5    68.8 2788.67    82.9 2785.72   108.7  2781.7   129.8 2775.59
     148 2774.38   157.9  2772.1   167.3  2771.1   177.7 2767.42   181.3 2766.83
  191.342767.402   195.4 2769.07   200.3 2769.96   203.2  2771.5     216 2779.55
   223.3 2783.61   238.1  2794.9   242.3 2797.77     247 2800.09   255.6 2803.43
   267.2 2807.12   270.4 2807.84   279.8 2808.08   287.6  2810.7   294.6 2812.22
#Mann= 3 ,-1,0
       0      .1       0   177.7    .045       0  191.34      .1       0
Bank Sta=177.7,191.34
XS Rating Curve= 0 ,0
Exp/Cntr(USF)=0,0
Exp/Cntr=0.3,0.1

Type RM Length L Ch R = 1 ,12757   ,72.8,72.9,74.1
XS GIS Cut Line= 3
2347329.45436174703432.7185167032347222.03519055 703470.63116536
 2347050.7261855703477.652026223
#Sta/Elev= 30
       0    2814     1.4 2813.47     9.8 2808.71    22.6 2806.02      48  2795.8
    70.3 2789.51    86.2 2786.03    98.6 2781.17   104.8 2778.42   111.6  2776.3
   119.8 2774.27   131.8 2773.14   139.8 2771.26   145.1 2770.86   151.8  2769.7
   159.8 2769.84   171.8 2766.95   183.8  2763.5  187.282763.106   191.8 2762.77
   199.8  2763.1   203.8 2764.05   207.9 2765.89   215.9 2770.93   225.8 2778.33
   231.9 2782.36   241.2 2786.88   247.9 2789.17   263.5 2791.22   285.4 2795.26
#Mann= 3 ,-1,0
       0      .1       0  187.28    .045       0   199.8      .1       0
Bank Sta=187.28,199.8
XS Rating Curve= 0 ,0
Exp/Cntr(USF)=0,0
Exp/Cntr=0.3,0.1

Type RM Length L Ch R = 1 ,12685   ,99.2,98.8,99.3
XS GIS Cut Line= 3
2347314.00846784703370.9349411132347216.41850186703404.635073253
 2347050.7261855 703397.61421239
#Sta/Elev= 30
       0 2817.45    10.4 2814.43    18.9 2811.17    31.6 2804.62    35.8 2803.48
    44.3 2802.21    52.7 2798.05    69.3  2791.5    73.9  2789.4    86.6 2782.14
   100.7 2773.52   111.5  2767.6   115.5 2766.43   123.5 2765.61   143.5 2766.25
   155.5 2764.32   167.5 2764.24   175.1 2760.77   179.6 2759.98   191.6 2759.25
  193.772759.827   203.6 2762.78   207.6 2765.62   211.6 2769.19   215.6  2771.9
   227.6 2778.45   231.6 2779.91   235.6    2781   251.6 2783.61   269.1 2784.61
#Mann= 3 ,-1,0
       0      .1       0   179.6    .045       0  193.77      .1       0
Bank Sta=179.6,193.77
XS Rating Curve= 0 ,0
Exp/Cntr(USF)=0,0
Exp/Cntr=0.3,0.1

Type RM Length L Ch R = 1 ,12586   ,109.3,103.6,96.1
XS GIS Cut Line= 4
2347262.68233449703274.9439111782347182.58618684703306.120260531
2347081.76991859703306.8496499652347039.24309084703387.271357535
#Sta/Elev= 30
       0 2818.15       7 2815.78    11.3 2813.93    28.4  2801.5    32.7 2798.67
    41.3 2795.81    45.6 2792.78    54.2 2785.35    68.5 2774.18    88.4 2760.21
    96.4 2755.32   100.4 2753.32   105.4 2752.79   112.4 2752.43   116.4 2752.77
   120.4 2753.79   128.4 2757.03   136.4 2759.16   140.4 2759.51   160.4 2757.24
   176.4 2758.14   180.4 2758.73   193.9  2762.3   207.5 2764.51   213.4 2766.49
   222.2 2770.13   241.5  2775.7   248.2 2777.99   270.9 2782.95   277.7 2783.76
#Mann= 3 ,-1,0
       0      .1       0   105.4    .045       0   116.4      .1       0
Bank Sta=105.4,116.4
XS Rating Curve= 0 ,0
Exp/Cntr(USF)=0,0
Exp/Cntr=0.3,0.1

Type RM Length L Ch R = 1 ,12482   ,111,110.7,110.4
XS GIS Cut Line= 2
 2347121.5865207703166.2442563092347008.03926478703386.404584589
#Sta/Elev= 30
       0 2797.17     3.3 2794.37     7.8 2791.98    15.1 2790.61    18.1 2789.29
    25.8 2783.26    46.7  2765.2    53.7 2760.56    66.3 2749.98    70.8 2747.36
   76.892746.145    79.8 2745.84    95.3 2746.13    97.8 2746.43   102.3 2747.78
   111.3 2752.08   115.8 2753.39   120.3  2754.2     125 2755.76   129.3 2757.75
   133.8 2758.37   147.3 2758.81   151.8 2759.97   157.6 2762.92   169.8 2768.03
   178.8 2771.02   190.3 2773.98   214.8 2779.31   223.8 2779.99   247.7 2782.89
#Mann= 3 ,0,0
       0      .1       0   76.89    .045       0    95.3      .1       0
Bank Sta=76.89,95.3
XS Rating Curve= 0 ,0
Exp/Cntr(USF)=0,0
Exp/Cntr=0.3,0.1

Type RM Length L Ch R = 1 ,12371   ,108.8,107.4,106.8
XS GIS Cut Line= 3
2347037.50954494703135.0404302542346994.17089764703168.844575147
2346918.76165134703341.332391398
#Sta/Elev= 30
       0 2787.27      11 2788.15    16.9 2786.36      22 2782.86    27.1 2778.51
    37.2 2767.74    42.5 2762.57    47.3 2759.51    59.7 2753.15    67.3 2747.76
    72.8 2742.74   76.812740.332      78    2740    87.1 2740.33      99 2740.53
   103.3 2741.33   129.5 2749.82   138.3 2751.58   151.4 2754.91   160.1 2756.13
   166.1 2758.27   173.2 2762.04   177.6  2763.6   186.3 2764.19   190.7  2765.1
   199.1 2768.74   203.8 2770.12   219.7 2771.94   225.6 2773.19   243.2 2779.06
#Mann= 3 ,-1,0
       0      .1       0   76.81    .045       0    87.1      .1       0
Bank Sta=76.81,87.1
XS Rating Curve= 0 ,0
Exp/Cntr(USF)=0,0
Exp/Cntr=0.3,0.1

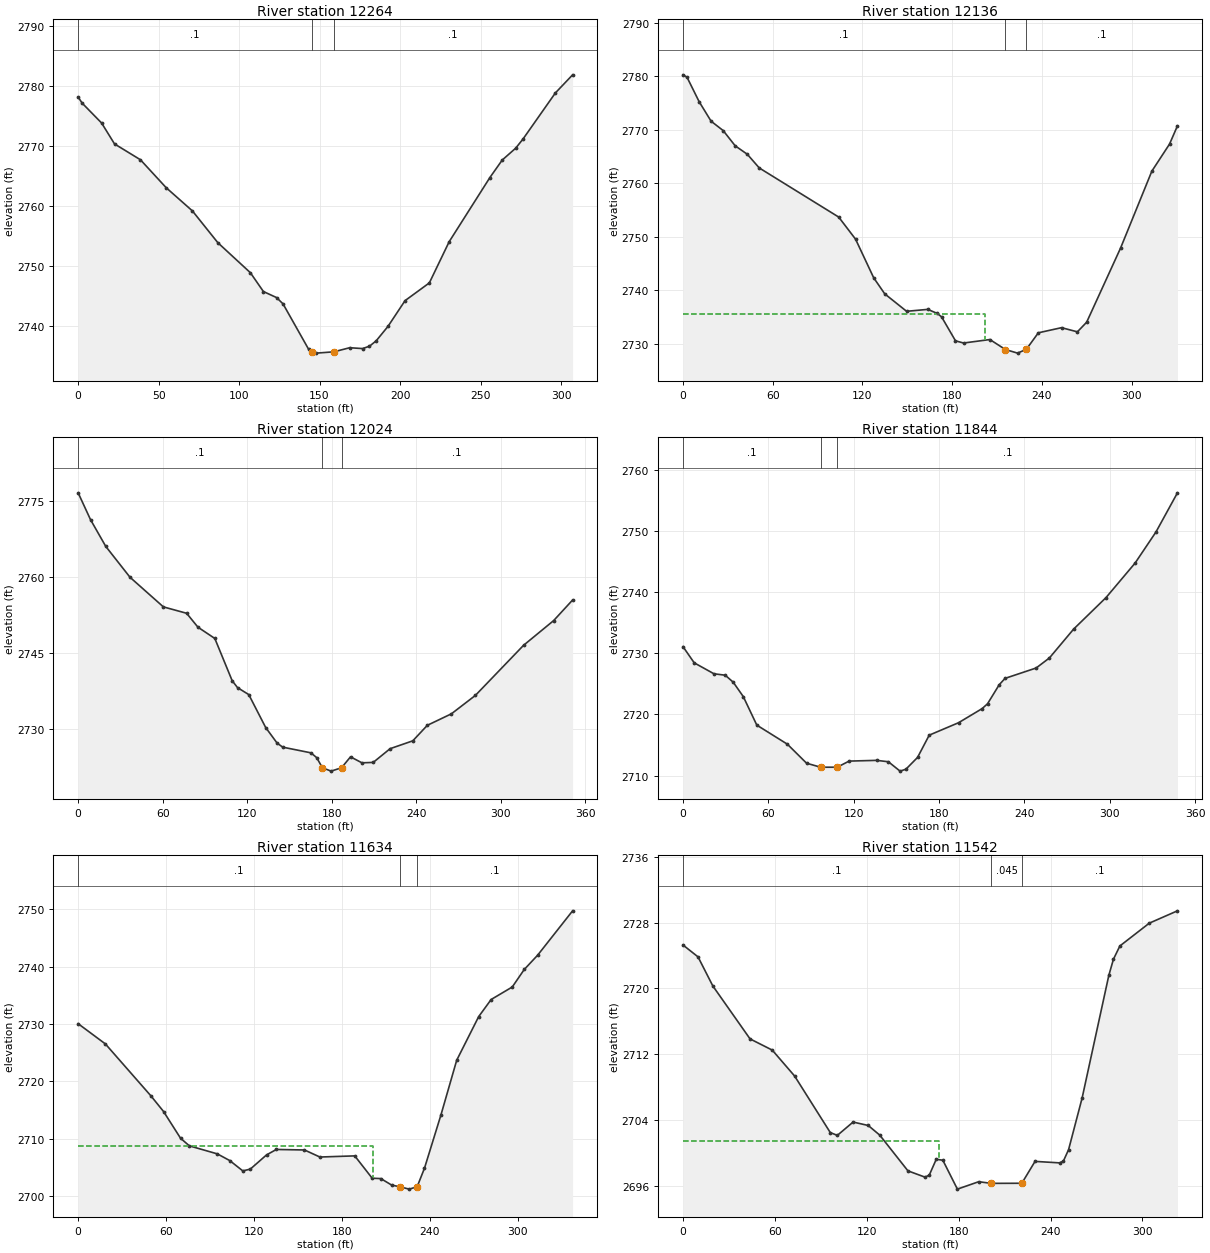
Type RM Length L Ch R = 1 ,12264   ,119.7,128.3,131.1
XS GIS Cut Line= 4
2346990.70380586703095.1688747382346894.49200886703102.969831252
2346888.42459823 703131.573338472346844.21917799703307.528246504
#Sta/Elev= 30
       0 2778.18     2.5 2777.17    14.6 2773.85    22.6 2770.37    38.7 2767.73
    54.7 2763.07      71  2759.2    86.8  2753.9     107  2748.9   115.1 2745.76
   123.3 2744.75   127.3  2743.7   143.2 2736.13  145.482735.701     148 2735.49
  158.872735.707   168.7 2736.39   176.7 2736.25     181 2736.64   185.2 2737.55
   192.5 2739.95   203.1 2744.24   218.2  2747.2   230.5 2754.06   255.8 2764.76
   263.5 2767.69   271.8 2769.65   276.4 2771.19   296.5 2778.87   307.2 2781.89
#Mann= 3 ,-1,0
       0      .1       0  145.48    .045       0  158.87      .1       0
Bank Sta=145.48,158.87
XS Rating Curve= 0 ,0
Exp/Cntr(USF)=0,0
Exp/Cntr=0.3,0.1

Type RM Length L Ch R = 1 ,12136   ,105.7,111.3,112.3
XS GIS Cut Line= 3
2346982.90284935703042.2957250332346851.15336156703057.030865115
2346679.53231825703155.842980957
#Sta/Elev= 30
       0 2780.29     2.7 2779.84    10.8 2775.27    18.8 2771.62    26.9 2769.86
    34.9 2767.02      43 2765.44      51 2762.88   104.1  2753.7   115.4 2749.56
   127.5 2742.35   134.9 2739.34   149.5 2736.08   163.7 2736.44     170 2735.68
   172.9 2735.04   182.2 2730.56   187.6 2730.15   205.2  2730.8  215.582728.932
   223.7 2728.26  229.582728.976   237.6 2732.06   253.1 2733.02   263.7 2732.24
   269.9 2734.04   292.6 2747.92   313.5 2762.29   325.3 2767.34   330.6 2770.75
#Mann= 3 ,-1,0
       0      .1       0  215.58    .045       0  229.58      .1       0
#XS Ineff= 2 , 0
          201.77 2735.49
Permanent Ineff=
       F       F
Bank Sta=215.58,229.58
XS Rating Curve= 0 ,0
Exp/Cntr(USF)=0,0
Exp/Cntr=0.3,0.1

Type RM Length L Ch R = 1 ,12024   ,186.8,180,171.4
XS GIS Cut Line= 3
2346956.89966097702980.7548458682346717.67032788 702999.82385068
2346639.66076274703078.700188765
#Sta/Elev= 30
       0 2776.56     8.8 2771.26    19.6 2765.99    36.8  2759.9    60.5 2754.05
      77 2752.79      85 2750.05      97 2747.82   109.3 2739.49   113.1 2738.12
   121.1 2736.74   133.1 2730.24   141.2 2727.17   145.2 2726.37   165.2 2725.25
   169.3  2724.3   173.3 2722.32   179.5 2721.64   186.9  2722.3   193.3 2724.46
   201.4 2723.28   209.4 2723.36   221.4 2726.07   237.5 2727.62   247.8 2730.68
   264.9 2732.95   281.9 2736.58   316.1 2746.47   337.5 2751.36   350.9 2755.41
#Mann= 3 ,-1,0
       0      .1       0   173.3    .045       0   186.9      .1       0
Bank Sta=173.3,186.9
XS Rating Curve= 0 ,0
Exp/Cntr(USF)=0,0
Exp/Cntr=0.3,0.1

Type RM Length L Ch R = 1 ,11844   ,206.4,210.9,213.3
XS GIS Cut Line= 4
2346757.54188339702759.7277446432346708.13582547702807.400256672
2346673.46490763702958.2187492732346592.85502365703052.697000385
#Sta/Elev= 30
       0 2731.07     7.9 2728.42    21.8 2726.63    29.7  2726.4    35.3 2725.26
    42.4  2722.9    51.9 2718.24    73.4 2715.12    86.9 2712.01    96.8 2711.36
   108.4 2711.36   116.8 2712.36   136.2 2712.48   144.4 2712.25   152.6 2710.72
   156.7 2711.03   164.9 2712.96   173.1  2716.6   193.7 2718.63   210.3 2720.94
   214.1 2721.73   222.3 2724.84   226.4 2725.88   248.3 2727.58   257.6 2729.22
   274.6 2733.93   297.4 2739.09   317.8 2744.72   332.5 2749.81   347.6 2756.21
#Mann= 3 ,-1,0
       0      .1       0    96.8    .045       0   108.4      .1       0
Bank Sta=96.8,108.4
XS Rating Curve= 0 ,0
Exp/Cntr(USF)=0,0
Exp/Cntr=0.3,0.1

Type RM Length L Ch R = 1 ,11634   ,90.3,91.8,92.6
XS GIS Cut Line= 2
2346687.33327477702718.1226432352346437.70266632702945.217155083
#Sta/Elev= 30
       0 2730.06    18.6 2726.53    49.7 2717.46    58.3 2714.74    69.9 2710.08
    75.9 2708.75      95 2707.35   103.5 2706.18   112.4 2704.38   117.5 2704.69
   128.6 2707.17   135.3 2708.12   154.5 2708.03     165  2706.8   188.8    2707
   200.7  2703.1   206.6 2703.04   213.9 2701.92   219.6  2701.6     226  2701.2
   231.4 2701.62   236.4 2704.85   247.6 2714.11   258.4 2723.69   273.4  2731.3
   281.9 2734.28   296.3 2736.46   304.5 2739.52   313.6    2742   337.5 2749.75
#Mann= 3 ,-1,0
       0      .1       0   219.6    .045       0   231.4      .1       0
#XS Ineff= 2 , 0
          201.12 2708.65
Permanent Ineff=
       F       F
Bank Sta=219.6,231.4
XS Rating Curve= 0 ,0
Exp/Cntr(USF)=0,0
Exp/Cntr=0.3,0.1

Type RM Length L Ch R = 1 ,11542   ,97,102.9,106.1
XS GIS Cut Line= 3
2346656.21717916702683.557606974 2346592.0911071702727.756976844
2346379.56232481702849.602889296
#Sta/Elev= 30
       0 2725.27     9.8 2723.83    19.5 2720.29    43.8 2713.86    58.3  2712.5
    72.9 2709.35    96.2 2702.48   100.8 2702.14   111.1 2703.76     121 2703.34
   128.5 2702.17   146.9 2697.83     158 2697.07   160.8  2697.3   165.4 2699.24
   169.7 2699.12   179.2 2695.61   193.1 2696.51   201.4 2696.31  221.282696.323
   229.9 2698.98   245.9  2698.8   248.4 2699.01   251.8  2700.4   260.6 2706.64
   278.1 2721.59   281.1 2723.54   285.3 2725.15   304.5 2727.92   322.9 2729.42
#Mann= 3 ,0,0
       0      .1       0   201.4    .045       0  221.28      .1       0
#XS Ineff= 2 , 0
          167.51 2701.41
Permanent Ineff=
       F       F
Bank Sta=201.4,221.28
XS Rating Curve= 0 ,0
Exp/Cntr(USF)=0,0
Exp/Cntr=0.3,0.1

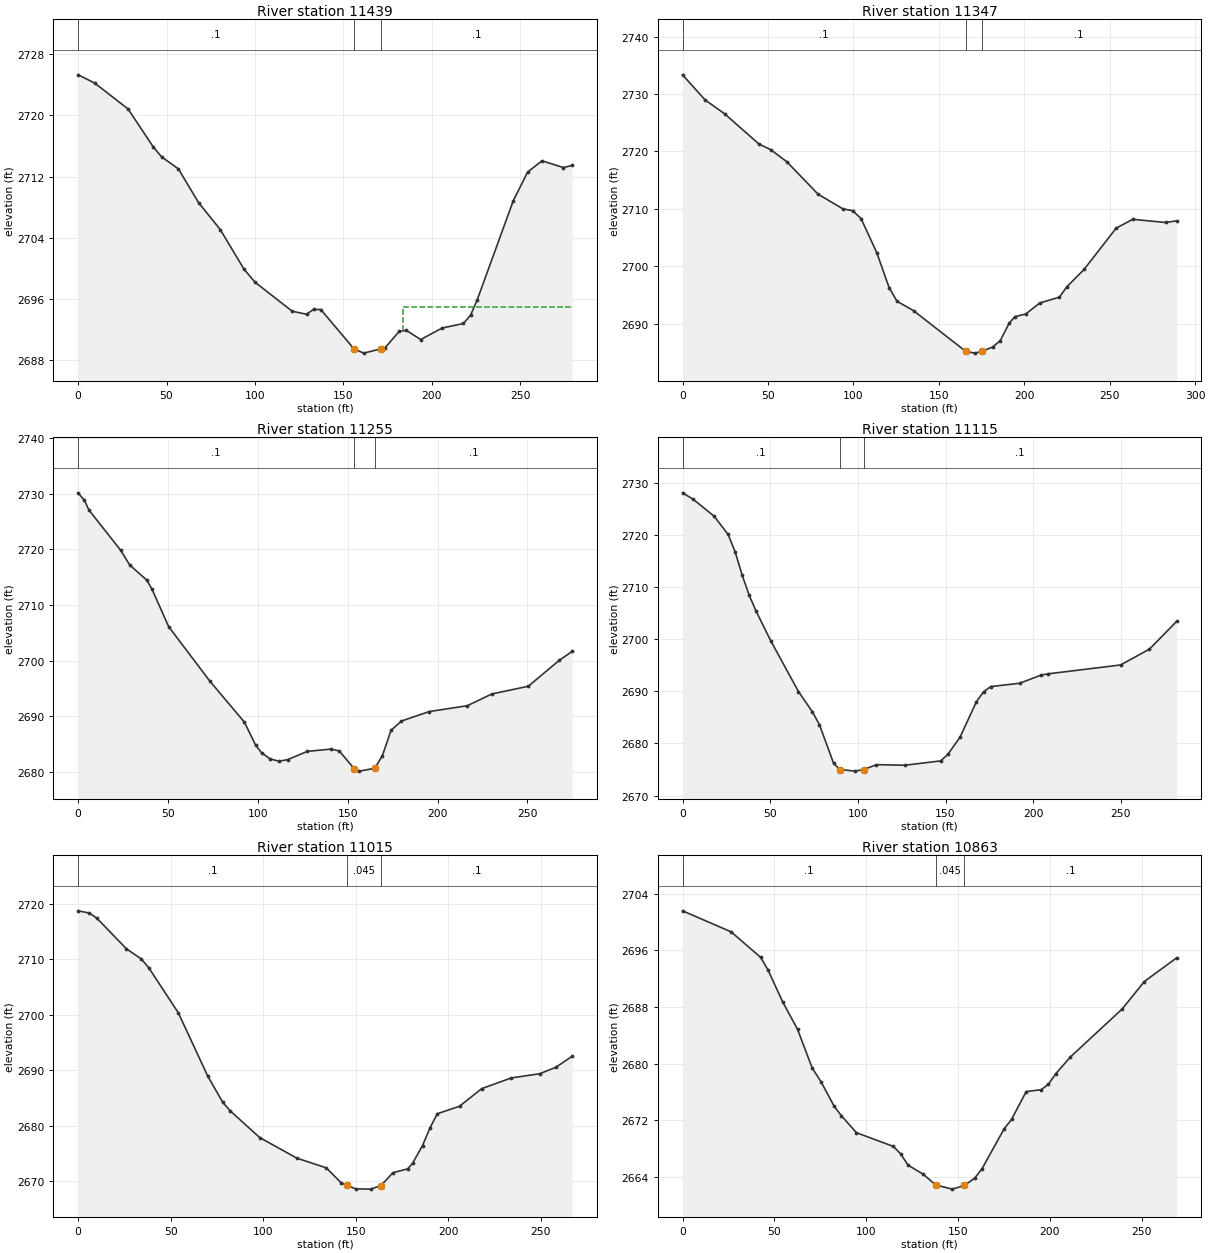
Type RM Length L Ch R = 1 ,11439   ,94.2,91.4,89.6
XS GIS Cut Line= 3
2346624.08305122702634.9003396692346531.32927043  702693.7894718
2346363.20859597702716.310442457
#Sta/Elev= 30
       0 2725.31     9.4 2724.23    28.3 2720.83    42.5 2715.88    47.3 2714.56
    56.7 2713.01    68.2 2708.57    80.4 2705.07    93.8  2699.9   100.1 2698.17
   121.1 2694.38   129.2 2693.99   133.2 2694.62   137.3  2694.6  155.982689.476
   161.5  2688.9171.07382689.446   173.6 2689.59   181.7 2691.76   185.7 2691.87
   193.8 2690.68   205.9 2692.18     218 2692.78     222 2693.87   225.8 2695.89
   246.2 2708.86   254.3 2712.59   262.4 2714.06   274.5 2713.18   279.5 2713.46
#Mann= 3 ,-1,0
       0      .1       0  155.98    .045       0171.0738      .1       0
#XS Ineff= 2 , 0
                          183.68         2694.93
Permanent Ineff=
       F       F
Bank Sta=155.98,171.0738
XS Rating Curve= 0 ,0
Exp/Cntr(USF)=0,0
Exp/Cntr=0.3,0.1

Type RM Length L Ch R = 1 ,11347   ,92.4,92.5,92.5
XS GIS Cut Line= 2
2346598.89520758702517.7982615112346358.79910154702679.018029464
#Sta/Elev= 30
       0 2733.34    13.2 2728.97    24.6 2726.56    44.8 2721.27    51.5 2720.33
    61.1 2718.19    79.3 2712.56    93.8 2710.01    99.6 2709.68   104.5  2708.3
   113.7 2702.36   120.9 2696.29   125.5 2693.92   135.2 2692.27   165.8 2685.18
   171.1 2684.88  175.162685.187   181.5 2685.94     186 2687.07   191.2 2690.12
   194.6 2691.24   200.8 2691.68   209.1 2693.61   220.6 2694.63   224.9 2696.42
     235 2699.45   253.8 2706.64   263.5 2708.18   282.7 2707.63   289.2 2707.91
#Mann= 3 ,-1,0
       0      .1       0   165.8    .045       0  175.16      .1       0
Bank Sta=165.8,175.16
XS Rating Curve= 0 ,0
Exp/Cntr(USF)=0,0
Exp/Cntr=0.3,0.1

Type RM Length L Ch R = 1 ,11255   ,148.8,140.1,133.7
XS GIS Cut Line= 3
2346537.20762825702449.2955544362346391.11695807702546.333882806
2346358.05994511702640.173145405
#Sta/Elev= 30
       0 2730.18     3.5 2728.82       6 2727.09    23.7 2719.84    28.7  2717.2
    38.2 2714.48    41.1 2712.84    50.4  2706.1    73.3  2696.3    92.5 2688.94
    98.8 2684.77   102.1 2683.41   106.9 2682.32   111.7 2681.91   116.5 2682.18
   127.6 2683.68   140.5 2684.08   145.3 2683.75   153.6 2680.57   156.5 2680.12
   165.1 2680.64   169.3 2682.91   174.1 2687.46   179.9 2689.13   195.4 2690.84
   216.6 2691.89   230.1 2693.99   250.5 2695.39   267.7 2700.06   274.9 2701.65
#Mann= 3 ,-1,0
       0      .1       0   153.6    .045       0   165.1      .1       0
Bank Sta=153.6,165.1
XS Rating Curve= 0 ,0
Exp/Cntr(USF)=0,0
Exp/Cntr=0.3,0.1

Type RM Length L Ch R = 1 ,11115   ,99.9,99.9,105.1
XS GIS Cut Line= 4
2346307.32492699702371.2110081322346302.52057953702454.757680663
2346317.03889091702532.6246095992346344.62149139702648.313199233
#Sta/Elev= 30
       0 2728.06       6 2726.84      18 2723.58      26 2720.07      30 2716.73
      34 2712.28      38 2708.42      42 2705.32    50.3 2699.68    66.1 2689.95
    74.1 2686.03    78.1 2683.56    86.1 2676.22    89.6 2674.99    98.4 2674.68
  103.36 2674.99   110.6 2675.92   126.8 2675.81   147.2 2676.64   151.3 2677.89
   158.2 2681.15   167.6 2687.99   171.7 2689.91   175.8  2690.9   192.2 2691.53
   204.6 2693.11   208.7 2693.35   249.8 2695.04   266.3 2698.08   281.8 2703.41
#Mann= 3 ,-1,0
       0      .1       0    89.6    .045       0  103.36      .1       0
Bank Sta=89.6,103.36
XS Rating Curve= 0 ,0
Exp/Cntr(USF)=0,0
Exp/Cntr=0.3,0.1

Type RM Length L Ch R = 1 ,11015   ,151.7,152.3,153.4
XS GIS Cut Line= 2
2346221.00942983702367.0796001122346223.60974866702634.045667475
#Sta/Elev= 30
       0 2718.79     6.1 2718.39    10.1 2717.47    26.1 2711.93    34.1 2710.11
    38.1 2708.55    54.1  2700.4    70.1 2688.91    78.1 2684.24    82.1 2682.69
    98.1 2677.85   118.1 2674.14   134.1 2672.37   142.1 2669.69  145.322669.187
   150.1 2668.58   158.1 2668.53   163.7 2669.18   170.1 2671.49   178.1 2672.19
   180.7 2673.18   186.1 2676.39   190.1 2679.56   194.1 2682.14   206.1  2683.5
   218.1 2686.68   234.1 2688.61   249.4 2689.37   258.1 2690.52     267 2692.53
#Mann= 3 ,-1,0
       0      .1       0  145.32    .045       0   163.7      .1       0
Bank Sta=145.32,163.7
XS Rating Curve= 0 ,0
Exp/Cntr(USF)=0,0
Exp/Cntr=0.3,0.1

Type RM Length L Ch R = 1 ,10863   ,129.2,133.3,141.3
XS GIS Cut Line= 2
2346084.05930436702374.8805566262346058.92288893702642.713396935
#Sta/Elev= 30
       0 2701.59    26.4 2698.63    42.5 2695.02    46.5 2693.25    54.5 2688.73
    62.6 2684.85    70.6 2679.37    75.5 2677.39    82.5    2674    86.5 2672.63
    94.7 2670.24   114.8  2668.3   118.8 2667.24   122.8 2665.65   130.9  2664.4
   137.9 2662.85   146.9 2662.27   153.4 2662.79     159 2663.81     163 2665.13
   175.1  2670.8   179.1 2672.11   187.1 2676.06   195.2 2676.31   199.2 2677.08
   203.2 2678.58   211.2 2680.95   239.3 2687.71   251.4  2691.6     269 2694.95
#Mann= 3 ,-1,0
       0      .1       0   137.9    .045       0   153.4      .1       0
Bank Sta=137.9,153.4
XS Rating Curve= 0 ,0
Exp/Cntr(USF)=0,0
Exp/Cntr=0.3,0.1

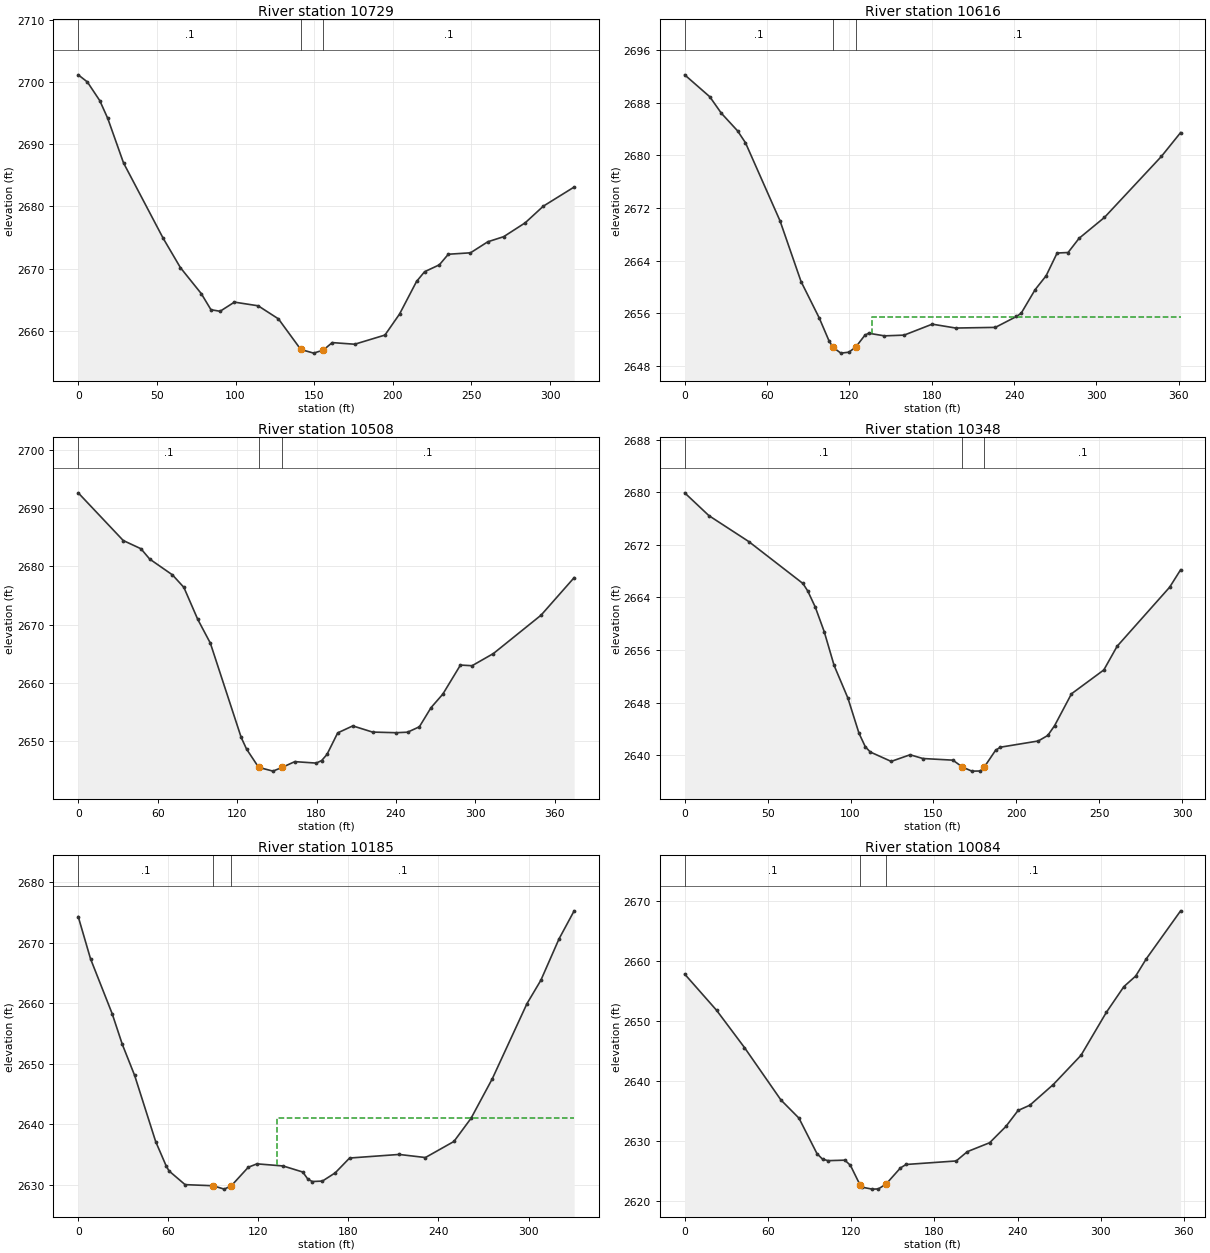
Type RM Length L Ch R = 1 ,10729   ,112.9,113.5,114.2
XS GIS Cut Line= 2
2346071.05771017 702369.679918952345820.56032878702561.236740012
#Sta/Elev= 30
       0 2701.12     5.8 2699.98    13.7 2696.98    18.8 2694.11    28.8 2686.98
      54 2674.88      65 2670.15    78.2    2666    84.4  2663.4    90.2 2663.15
    99.3 2664.62   114.4 2664.03   127.3 2661.93   141.5 2657.02   149.7 2656.43
   155.8 2656.92   161.5 2658.12   175.8 2657.86     195 2659.33   204.3 2662.71
   215.1 2667.94   220.2  2669.5   229.6 2670.61   235.3 2672.31   249.4 2672.54
   260.4 2674.31   270.5 2675.13   284.2 2677.36   295.7 2680.03   315.3  2683.1
#Mann= 3 ,-1,0
       0      .1       0   141.5    .045       0   155.8      .1       0
Bank Sta=141.5,155.8
XS Rating Curve= 0 ,0
Exp/Cntr(USF)=0,0
Exp/Cntr=0.3,0.1

Type RM Length L Ch R = 1 ,10616   ,113.7,107.6,99.4
XS GIS Cut Line= 3
2345982.64686968702306.4054938932345776.35490854702439.021754628
2345778.95522738 702555.16932939
#Sta/Elev= 30
       0 2692.27    18.3 2688.93    26.7 2686.43    38.5 2683.75    44.3 2681.93
    69.5 2670.03    84.8  2660.8      98 2655.28   105.1 2651.81     108  2650.8
   113.8  2649.9   119.6 2650.04   124.62650.809   131.3 2652.62     134 2652.93
   145.6 2652.53   159.9 2652.64   180.4 2654.31   197.5 2653.72   226.4 2653.82
   241.8 2655.48   245.2 2655.97   255.4 2659.57   263.4 2661.68   271.4 2665.14
   279.4 2665.22   287.4 2667.38   305.9 2670.56   347.4 2679.85   361.4 2683.48
#Mann= 3 ,-1,0
       0      .1       0     108    .045       0   124.6      .1       0
#XS Ineff= 2 , 0
                          136.66          2655.4
Permanent Ineff=
       F       F
Bank Sta=108,124.6
XS Rating Curve= 0 ,0
Exp/Cntr(USF)=0,0
Exp/Cntr=0.3,0.1

Type RM Length L Ch R = 1 ,10508   ,158.9,160,164.2
XS GIS Cut Line= 4
2345865.44918501702198.9352341612345802.15520198702285.564322439
2345787.60366039702376.5016050422345712.47751746702534.828662992
#Sta/Elev= 30
       0 2692.65      34 2684.46    47.4 2683.04      54 2681.27    71.2 2678.55
    79.8 2676.41    90.3 2670.91    99.8 2666.83   123.1 2650.63   127.2 2648.61
  136.292645.489   147.1 2644.84   154.1 2645.49   163.6 2646.47   179.8 2646.22
   183.9 2646.66   187.9 2647.71     196 2651.41   207.4 2652.61   222.3 2651.55
     240 2651.44   248.8 2651.53   257.7 2652.46   266.5 2655.75   275.4 2658.07
   288.7 2663.06   297.5 2662.95   313.6 2665.04   349.6 2671.63   374.6 2678.08
#Mann= 3 ,0,0
       0      .1       0  136.29    .045       0   154.1      .1       0
Bank Sta=136.29,154.1
XS Rating Curve= 0 ,0
Exp/Cntr(USF)=0,0
Exp/Cntr=0.3,0.1

Type RM Length L Ch R = 1 ,10348   ,165.8,163.2,163.7
XS GIS Cut Line= 2
2345742.33882762 702181.367084262345565.56752659702422.473518657
#Sta/Elev= 30
       0 2679.93    14.6 2676.46    38.6 2672.52    71.3 2666.13    74.2 2664.99
    78.7 2662.56    84.1 2658.82    90.1 2653.65    98.4 2648.69   105.1 2643.33
   108.9 2641.28   111.9 2640.48   124.5 2639.05   135.9 2640.06   143.6 2639.49
   161.7 2639.24   167.4  2638.2   173.1 2637.57   178.3 2637.59  180.692638.215
   187.4 2640.73   190.3 2641.21   213.2 2642.16   218.9    2643     223 2644.48
   233.2 2649.34   252.7 2652.97   260.7 2656.57   292.4 2665.57     299 2668.22
#Mann= 3 ,-1,0
       0      .1       0   167.4    .045       0  180.69      .1       0
Bank Sta=167.4,180.69
XS Rating Curve= 0 ,0
Exp/Cntr(USF)=0,0
Exp/Cntr=0.3,0.1

Type RM Length L Ch R = 1 ,10185   ,104.2,101.3,97
XS GIS Cut Line= 3
2345646.73802196702117.6332138212345591.42183252702144.088782682
2345484.99829415702391.207846366
#Sta/Elev= 30
       0 2674.29     8.2 2667.33    22.6 2658.29    29.4  2653.2    37.6 2648.09
    51.6 2637.19    58.6 2633.17    60.5 2632.34    71.2 2630.08    89.8  2629.9
    97.3 2629.34  101.962629.879   113.3 2632.95   119.1 2633.51   136.5 2633.16
   149.6 2632.16   152.9 2631.02   155.9 2630.59   162.7 2630.67   171.2 2632.02
   180.8 2634.47   213.8 2635.06   231.3 2634.55   250.3  2637.2   261.7 2641.02
   275.9 2647.56     299 2659.95   308.2 2663.78   320.3  2670.6   330.4 2675.24
#Mann= 3 ,-1,0
       0      .1       0    89.8    .045       0  101.96      .1       0
#XS Ineff= 2 , 0
                          132.17            2641
Permanent Ineff=
       F       F
Bank Sta=89.8,101.96
XS Rating Curve= 0 ,0
Exp/Cntr(USF)=0,0
Exp/Cntr=0.3,0.1

Type RM Length L Ch R = 1 ,10084   ,114.4,115.3,118.3
XS GIS Cut Line= 4
2345533.09932844702052.0955545952345475.37808729702115.829425034
2345488.60587172702261.9363167022345447.11872964702379.783850721
#Sta/Elev= 30
       0 2657.78      23 2651.74    43.1 2645.53    69.4 2636.78    82.4 2633.75
    95.4 2627.83    99.4 2626.91   103.4 2626.66   115.5 2626.74   119.5 2625.88
   126.3 2622.68   127.5 2622.25   135.2 2621.91   139.6 2621.94  145.18 2622.75
   155.6 2625.45   159.6 2626.02   195.8 2626.61   203.8 2628.16   219.9 2629.65
   231.6 2632.36   240.4 2635.03   248.9 2635.91   265.8 2639.36   285.8 2644.24
     304 2651.38   316.7 2655.69   325.2 2657.45   332.8 2660.31   357.6 2668.33
#Mann= 3 ,-1,0
       0      .1       0   126.3    .045       0  145.18      .1       0
Bank Sta=126.3,145.18
XS Rating Curve= 0 ,0
Exp/Cntr(USF)=0,0
Exp/Cntr=0.3,0.1