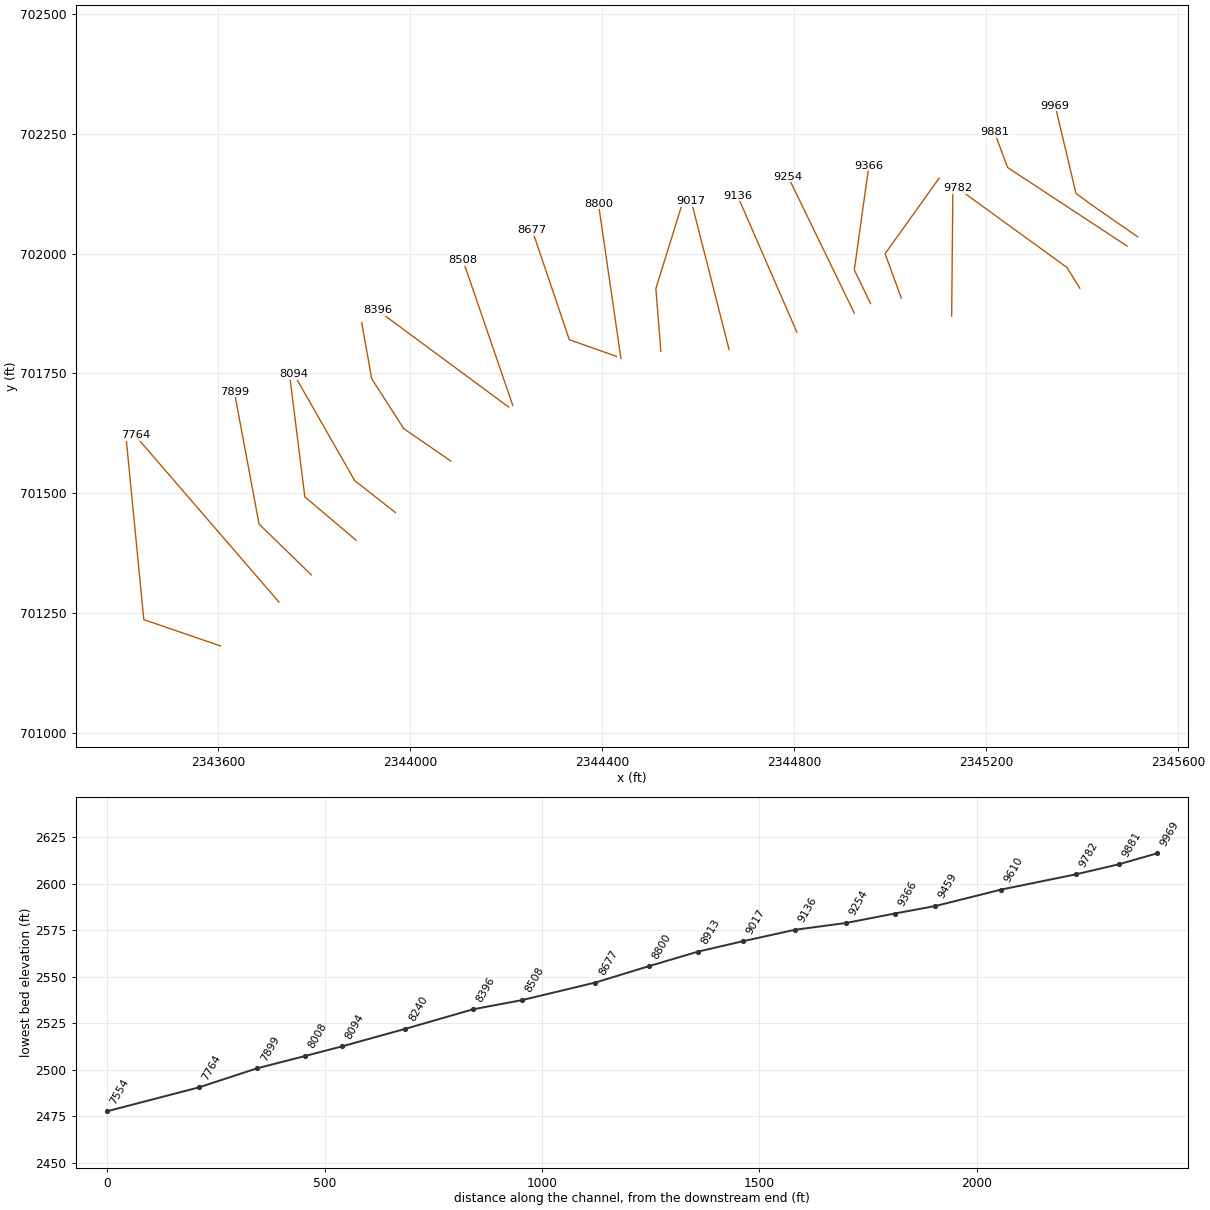
HEC-RAS study TAYLORRN.prj: TAYLORRN

--- TAYLORRN.g01 (geometry) --- (continued)

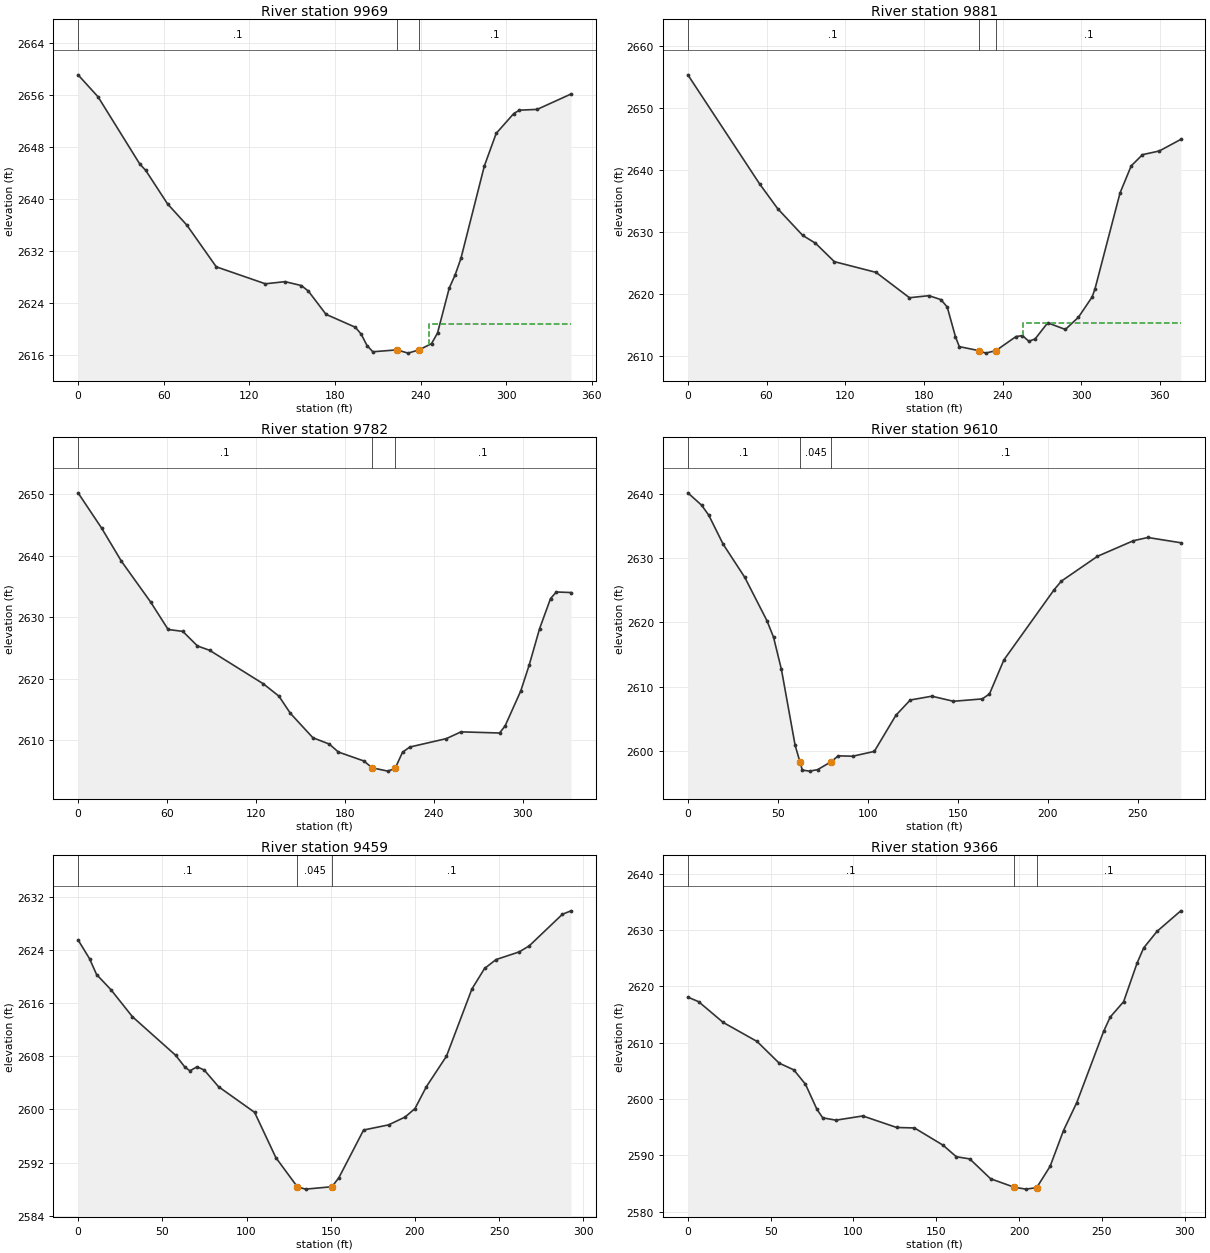
Type RM Length L Ch R = 1 ,9969    ,83.8,87.3,94.9
XS GIS Cut Line= 4
2345515.66270351702034.6589296642345418.85937199702102.000377675
2345386.99243678702125.4496318932345343.70150591 702308.23356221
#Sta/Elev= 30
       0 2659.06      14 2655.68    43.2 2645.37    47.4 2644.38    62.7 2639.23
    76.2 2635.98    96.8 2629.57   131.2 2626.96     145 2627.29   156.4 2626.69
   161.3 2625.85   173.7 2622.27   194.2 2620.29   198.3 2619.24   202.4 2617.48
   206.5 2616.52   223.4 2616.81   231.2 2616.31   239.1 2616.83   247.6 2617.77
   251.8 2619.39     260 2626.29   264.1  2628.3   268.2 2630.85   284.6 2645.05
   292.9 2650.06   305.2 2653.11   309.2 2653.63   321.6 2653.75   345.3 2656.11
#Mann= 3 ,-1,0
       0      .1       0   223.4    .045       0   239.1      .1       0
#XS Ineff= 2 , 0
                          245.76         2620.81
Permanent Ineff=
       F       F
Bank Sta=223.4,239.1
XS Rating Curve= 0 ,0
Exp/Cntr(USF)=0,0
Exp/Cntr=0.3,0.1

Type RM Length L Ch R = 1 ,9881    ,99.7,99.6,99.1
XS GIS Cut Line= 3
2345493.35000922702015.6150996242345244.58617372702179.435186415
2345217.36499793702252.556008571
#Sta/Elev= 30
       0 2655.37    54.7 2637.78    68.5 2633.78    87.6 2629.46    97.3 2628.21
   111.7 2625.23   143.5  2623.5     169 2619.41   183.9 2619.74     193  2619.1
   197.8 2617.91   204.1  2613.1     207 2611.52   221.7 2610.88   227.2 2610.47
  234.992610.885   250.3 2613.15   255.2 2613.29     260 2612.39   264.8 2612.75
   274.4 2615.36   287.9 2614.29   297.9 2616.27   308.3 2619.53   310.5 2620.85
   329.6 2636.32   338.1 2640.68   346.7 2642.49   359.5 2643.08   375.9 2644.95
#Mann= 3 ,-1,0
       0      .1       0   221.7    .045       0  234.99      .1       0
#XS Ineff= 2 , 0
                          255.44          2615.3
Permanent Ineff=
       F       F
Bank Sta=221.7,234.99
XS Rating Curve= 0 ,0
Exp/Cntr(USF)=0,0
Exp/Cntr=0.3,0.1

Type RM Length L Ch R = 1 ,9782    ,182.5,171.4,166.5
XS GIS Cut Line= 3
 2345394.9748123701927.6257164982345368.10485098701970.964363797
2345140.14356618 702136.51799648
#Sta/Elev= 30
       0 2650.21    15.9 2644.48    29.3 2639.09    48.9 2632.51    60.8 2628.02
    70.7 2627.71    80.6 2625.34    88.8 2624.64   125.1 2619.19   135.6 2617.19
   143.3 2614.41   158.5 2610.44   169.6 2609.41   175.7 2608.12   192.9 2606.67
   198.52605.558   209.1 2605.02     214 2605.46     219 2608.09   223.9 2608.93
   248.6  2610.3   258.5  2611.4   284.5 2611.21   288.2 2612.35   298.8 2618.04
   304.5 2622.25   311.5 2628.14   318.9 2633.04   322.8 2634.11   332.7 2634.02
#Mann= 3 ,-1,0
       0      .1       0   198.5    .045       0     214      .1       0
Bank Sta=198.5,214
XS Rating Curve= 0 ,0
Exp/Cntr(USF)=0,0
Exp/Cntr=0.3,0.1

Type RM Length L Ch R = 1 ,9610    ,158.2,151.3,148.5
XS GIS Cut Line= 2
2345128.00874494701869.5519291172345130.60906378702143.452180048
#Sta/Elev= 30
       0 2640.15     7.6 2638.24    11.6 2636.68    19.6 2632.16    31.6 2627.01
    43.9 2620.28    47.6 2617.69      52 2612.66    59.6 2600.87   62.292598.277
    63.6    2597    67.6 2596.84    72.1 2597.07    79.6  2598.3    83.6 2599.22
    91.6 2599.16   103.6 2599.91   115.6 2605.53   123.6 2607.91   135.6  2608.5
   147.6 2607.71   163.6 2608.08   167.6 2608.85   175.6 2614.14   203.6  2625.1
   207.6 2626.42   227.6 2630.27   247.6  2632.7   255.6  2633.2   273.9 2632.38
#Mann= 3 ,-1,0
       0      .1       0   62.29    .045       0    79.6      .1       0
Bank Sta=62.29,79.6
XS Rating Curve= 0 ,0
Exp/Cntr(USF)=0,0
Exp/Cntr=0.3,0.1

Type RM Length L Ch R = 1 ,9459    ,89.6,93.1,95.4
XS GIS Cut Line= 3
2345023.12921848701906.8231657942344989.32507358701999.567871014
2345102.00555656702157.320547184
#Sta/Elev= 30
       0 2625.52     6.8  2622.7      11 2620.31    19.5 2618.03    32.3 2613.95
    57.9 2608.16    63.4 2606.38    66.4 2605.81    70.6 2606.42    74.9 2605.93
    83.4 2603.42   104.8 2599.56   117.4 2592.75   130.2 2588.34   135.1    2588
   150.7 2588.36   154.8 2589.71   169.5  2596.9   184.3 2597.67   194.1 2598.85
     200 2600.13   206.8 2603.44   218.7 2608.02   233.8 2618.14   241.3 2621.22
   248.1 2622.56   261.9 2623.72   267.8 2624.62   287.5 2629.38   292.6  2629.9
#Mann= 3 ,-1,0
       0      .1       0   130.2    .045       0   150.7      .1       0
Bank Sta=130.2,150.7
XS Rating Curve= 0 ,0
Exp/Cntr(USF)=0,0
Exp/Cntr=0.3,0.1

Type RM Length L Ch R = 1 ,9366    ,107.5,111.7,115.6
XS GIS Cut Line= 3
2344958.98802047701895.5551174962344925.18387558701965.763726121
2344955.52092869702183.323735563
#Sta/Elev= 30
       0 2618.09     6.5 2617.28    21.3  2613.6    41.8 2610.21    55.1 2606.37
      64 2605.16      71 2602.62    77.9 2598.18    81.4 2596.65    89.4 2596.23
   105.6 2596.98   126.1 2594.93   136.8 2594.85   154.1 2591.78   162.1 2589.73
   170.2 2589.35   182.8 2585.82     197 2584.32   204.1 2583.98   210.6 2584.24
   218.7 2588.03   226.8 2594.39   234.8 2599.35     251 2611.99     255 2614.55
   263.1 2617.28   271.2 2624.12   275.2 2626.83   283.3 2629.78   297.6 2633.42
#Mann= 3 ,-1,0
       0      .1       0     197    .045       0   210.6      .1       0
Bank Sta=197,210.6
XS Rating Curve= 0 ,0
Exp/Cntr(USF)=0,0
Exp/Cntr=0.3,0.1

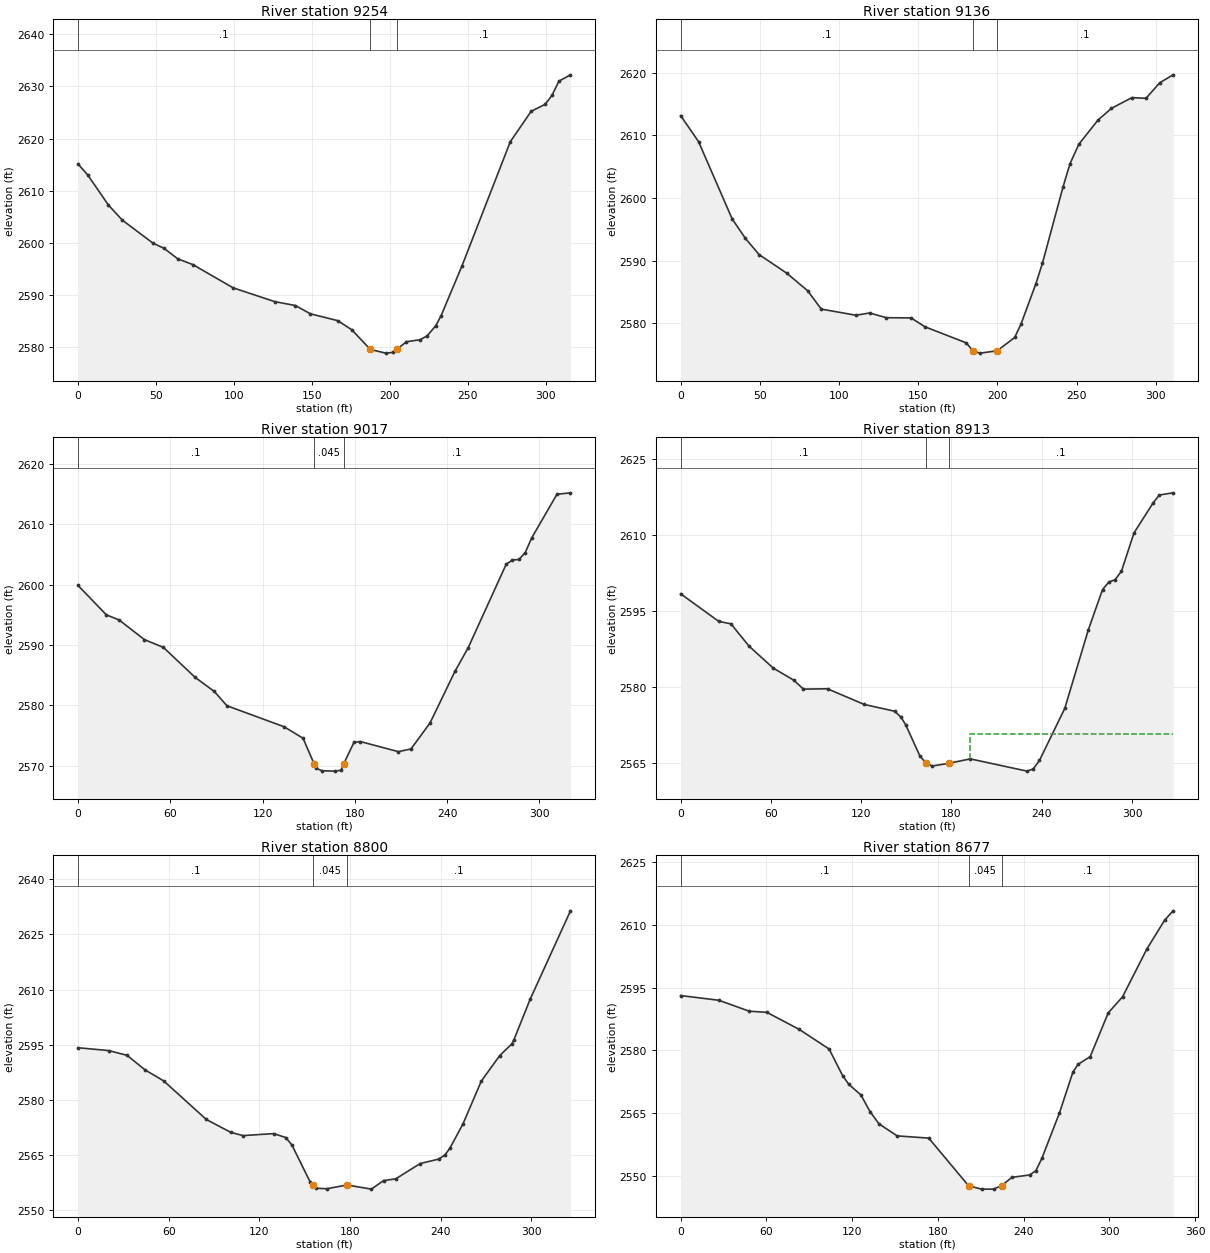
Type RM Length L Ch R = 1 ,9254    ,118.4,118.3,117.6
XS GIS Cut Line= 2
2344925.18387558701875.6193397392344787.36697717702159.920866021
#Sta/Elev= 30
       0 2615.13     6.2 2613.04    19.5 2607.27    28.4 2604.38    48.2 2599.95
    55.1    2599      64 2596.97    73.8 2595.85    99.5 2591.42   126.2 2588.78
   139.5 2588.03     149 2586.45   166.6 2585.14   175.6 2583.39   187.5 2579.63
   197.3 2578.92   201.8 2579.05   204.42579.634   210.7  2581.1   219.5 2581.49
     224 2582.24   229.5 2584.18   232.9 2586.09   246.2 2595.55   277.3  2619.4
   290.7 2625.22   299.6 2626.54     304 2628.25   308.5 2630.99   315.9  2632.2
#Mann= 3 ,-1,0
       0      .1       0   187.5    .045       0   204.4      .1       0
Bank Sta=187.5,204.4
XS Rating Curve= 0 ,0
Exp/Cntr(USF)=0,0
Exp/Cntr=0.3,0.1

Type RM Length L Ch R = 1 ,9136    ,121,119.3,117.4
XS GIS Cut Line= 2
2344805.56920904701835.7477842232344681.62067776702120.916083452
#Sta/Elev= 30
       0 2613.15    11.3 2608.99    32.5 2596.66    40.8 2593.57    49.5 2590.96
      67 2587.98    80.1  2585.2    88.8 2582.25   110.6 2581.27   119.3 2581.63
   129.8 2580.88   145.5 2580.84   154.2 2579.43   180.4 2576.85   184.6 2575.56
   189.1 2575.22   199.8 2575.59   210.9 2577.72     215 2579.94   224.3 2586.32
   228.4 2589.56   241.4 2601.75   245.8 2605.46   251.4 2608.58   263.6 2612.47
     272 2614.31   284.9 2616.02   293.8 2615.91   302.5  2618.4   310.9 2619.66
#Mann= 3 ,-1,0
       0      .1       0   184.6    .045       0   199.8      .1       0
Bank Sta=184.6,199.8
XS Rating Curve= 0 ,0
Exp/Cntr(USF)=0,0
Exp/Cntr=0.3,0.1

Type RM Length L Ch R = 1 ,9017    ,107.7,103.3,98
XS GIS Cut Line= 2
2344664.28521884701799.3433204922344585.40888076702109.648035154
#Sta/Elev= 30
       0 2599.88    18.4 2595.01    26.7 2594.16    43.2 2590.89    55.5 2589.61
    76.2 2584.62    88.6  2582.3    96.8 2579.93     134 2576.44   146.3 2574.54
  153.462570.307   154.6 2569.58   158.7 2569.14     167 2569.08   171.1 2569.23
   172.7 2570.28   179.4 2573.84   183.5 2573.99   208.3 2572.31   216.5 2572.76
   228.9 2577.08   245.1 2585.64   253.7 2589.56   278.4  2603.4   282.5 2604.11
   286.7 2604.19   290.8 2605.34   294.9 2607.74   311.4 2615.01   320.2 2615.25
#Mann= 3 ,-1,0
       0      .1       0  153.46    .045       0   172.7      .1       0
Bank Sta=153.46,172.7
XS Rating Curve= 0 ,0
Exp/Cntr(USF)=0,0
Exp/Cntr=0.3,0.1

Type RM Length L Ch R = 1 ,8913    ,110.8,113.7,117
XS GIS Cut Line= 3
 2344522.1344557701795.8762287082344511.73318035701926.758943552
2344569.80696773702113.981899884
#Sta/Elev= 30
       0 2598.38    25.4 2592.94    33.4 2592.48    45.4  2588.1    61.5 2583.77
    75.2 2581.38    81.6 2579.63    97.6 2579.69     122 2576.61   142.2 2575.28
   146.4 2574.13   149.6 2572.59     159 2566.48   163.1 2565.07   167.3  2564.5
   178.3 2565.03   192.5  2565.9   230.2 2563.49   234.3 2563.91   238.5 2565.59
   255.3 2575.84     271 2591.32   280.4 2599.22   284.6 2600.69   288.8 2601.17
     293 2602.84   301.3 2610.36   313.9 2616.21   318.1 2617.82   327.3 2618.25
#Mann= 3 ,-1,0
       0      .1       0   163.1    .045       0   178.3      .1       0
#XS Ineff= 2 , 0
                          192.56         2570.86
Permanent Ineff=
       F       F
Bank Sta=163.1,178.3
XS Rating Curve= 0 ,0
Exp/Cntr(USF)=0,0
Exp/Cntr=0.3,0.1

Type RM Length L Ch R = 1 ,8800    ,119.6,122.5,123.9
XS GIS Cut Line= 2
2344438.92425288701781.141088626 2344392.1185138702103.580624532
#Sta/Elev= 30
       0 2594.14    20.2 2593.37    32.4 2592.08    44.5 2588.06    56.6 2585.13
    84.9 2574.59   101.1 2571.08   109.2  2570.2   129.4 2570.75   137.5 2569.66
   141.5 2567.63   153.6 2557.55   155.62556.704   157.7 2555.85   164.8 2555.73
   177.9 2556.75   194.1 2555.62   202.1 2557.94   210.2 2558.42   226.4  2562.6
   238.5 2563.79   242.6 2564.87     246 2566.75   254.7 2573.42   266.8 2585.04
   278.9 2591.95     287  2595.2   288.4 2596.33   299.1 2607.33   325.8 2631.44
#Mann= 3 ,-1,0
       0      .1       0   155.6    .045       0   177.9      .1       0
Bank Sta=155.6,177.9
XS Rating Curve= 0 ,0
Exp/Cntr(USF)=0,0
Exp/Cntr=0.3,0.1

Type RM Length L Ch R = 1 ,8677    ,166.1,168.6,167.3
XS GIS Cut Line= 3
2344429.38975048701785.4749533562344331.44440758701820.145871196
2344254.30161539702048.107155989
#Sta/Elev= 30
       0 2593.12    26.7 2591.99      48 2589.38    60.3 2589.11      83 2585.03
   103.9 2580.34   113.4 2573.95   117.7 2571.89   126.1 2569.39   132.5  2565.4
   138.8 2562.46   151.5 2559.59   173.6 2559.06   201.5 2547.67   210.6 2546.87
     219 2546.87  224.792547.726   231.7 2549.68   244.3 2550.26   248.6 2551.29
   252.8 2554.24   265.1 2565.09   274.5 2574.84   278.1 2576.68   286.6 2578.53
   299.2 2588.97   309.2  2592.8   326.2 2604.21   338.7 2611.14   344.6 2613.36
#Mann= 3 ,-1,0
       0      .1       0   201.5    .045       0  224.79      .1       0
Bank Sta=201.5,224.79
XS Rating Curve= 0 ,0
Exp/Cntr(USF)=0,0
Exp/Cntr=0.3,0.1

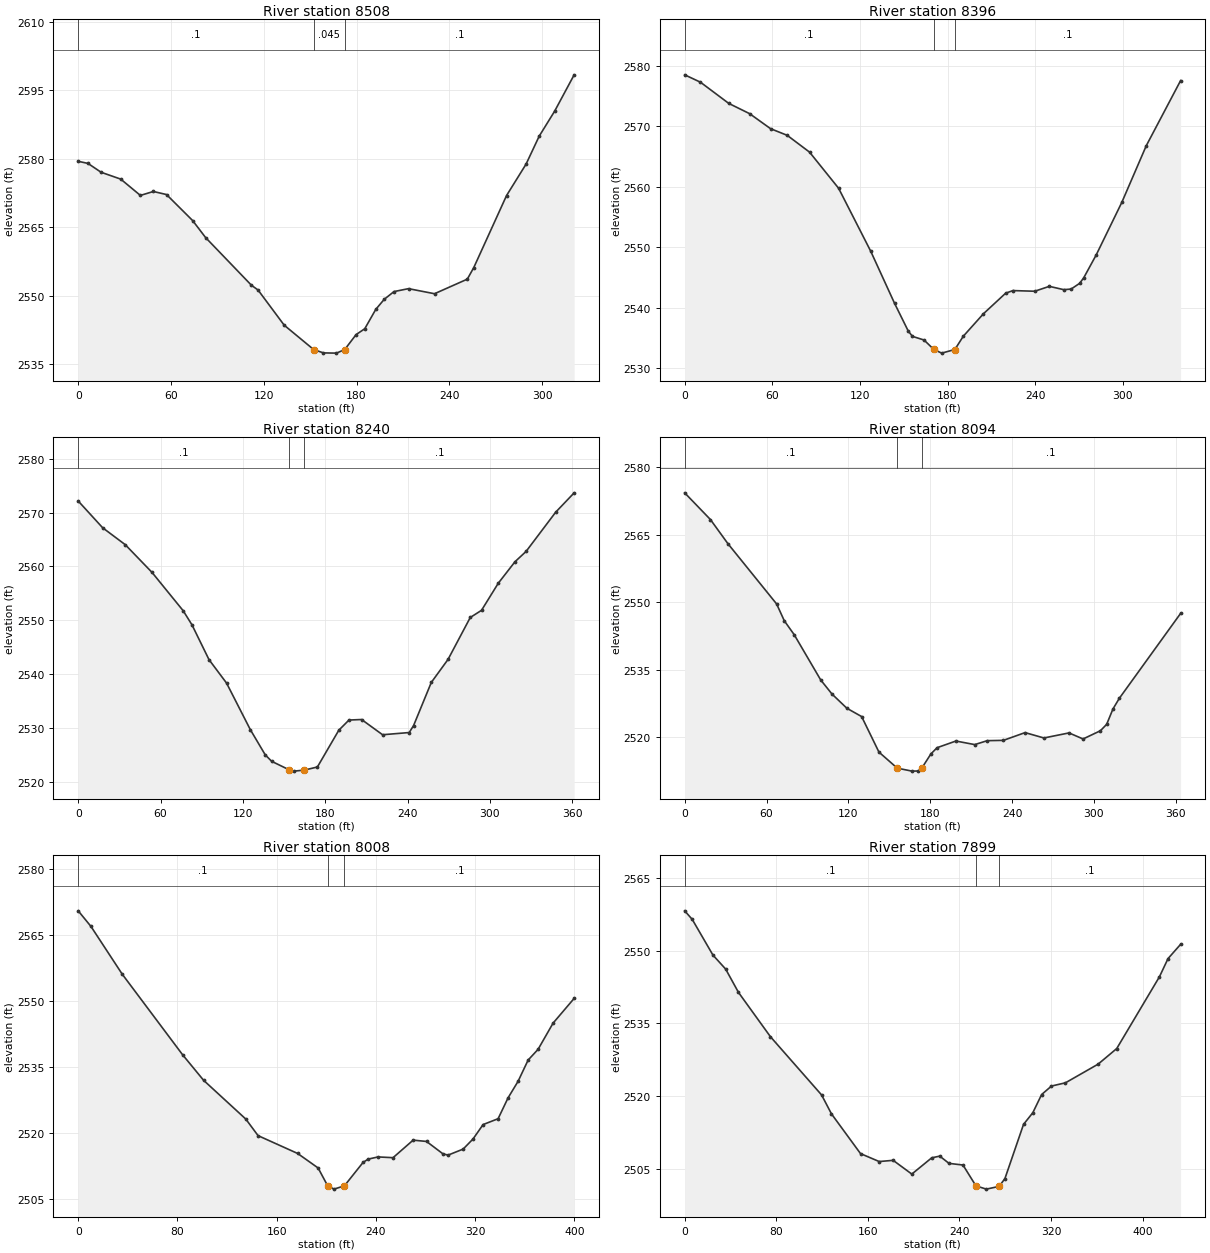
Type RM Length L Ch R = 1 ,8508    ,107.7,112.4,117.1
XS GIS Cut Line= 2
2344213.56328693 701683.195745732344109.55053341701986.566276825
#Sta/Elev= 30
       0 2579.43     6.3 2578.97    14.8 2577.03    27.5 2575.53    40.2 2571.96
    48.6 2572.82    57.1 2572.15      74 2566.45    82.4 2562.72     112 2552.29
   116.3 2551.24   133.2 2543.54   152.3 2538.19   158.6 2537.47     167 2537.42
  172.312538.197   179.7 2541.48   185.3 2542.76   192.4 2546.99   197.9 2549.21
   204.2  2550.9   213.6 2551.54   230.4 2550.43   251.6 2553.62   255.8 2556.16
     277 2571.94   289.6 2578.81   298.1 2584.94   308.1 2590.42   320.7 2598.37
#Mann= 3 ,-1,0
       0      .1       0   152.3    .045       0  172.31      .1       0
Bank Sta=152.3,172.31
XS Rating Curve= 0 ,0
Exp/Cntr(USF)=0,0
Exp/Cntr=0.3,0.1

Type RM Length L Ch R = 1 ,8396    ,158.6,156.2,154.5
XS GIS Cut Line= 2
2344204.89555747701679.7286539462343931.86207948 701881.68675036
#Sta/Elev= 30
       0 2578.53    10.8 2577.31    30.2  2573.8    44.5  2572.1    58.8 2569.62
    70.2 2568.52    85.5 2565.74   105.4 2559.76   127.4 2549.34   143.7 2540.73
   153.1 2536.13     156 2535.25   163.9 2534.65   170.6 2533.09     176 2532.48
     185 2533.08   190.8 2535.28   204.6    2539   219.8  2542.4   224.8 2542.83
   239.7 2542.72   249.7 2543.53   259.6 2542.98   264.6 2543.08   270.4 2544.02
   273.2 2544.92   281.8 2548.73   299.4 2557.46   316.1 2566.81   339.6 2577.58
#Mann= 3 ,-1,0
       0      .1       0   170.6    .045       0     185      .1       0
Bank Sta=170.6,185
XS Rating Curve= 0 ,0
Exp/Cntr(USF)=0,0
Exp/Cntr=0.3,0.1

Type RM Length L Ch R = 1 ,8240    ,146.6,145.8,144.3
XS GIS Cut Line= 4
2344084.41411798701567.0481709682343986.46877508701634.656460755
2343919.72725824701738.6692142732343898.92470754701855.683561981
#Sta/Elev= 30
       0 2572.16    17.8 2567.19    34.3 2564.04    53.8 2558.89    76.5 2551.77
    82.9 2549.15    95.3 2542.69   108.1 2538.33   125.4 2529.69   136.3 2524.99
     141 2523.79   153.92522.193   157.2 2521.97   164.8 2522.16   174.3 2522.74
   189.9 2529.57   197.3 2531.46   206.5 2531.56   221.8 2528.73   241.2 2529.14
   244.4 2530.44   257.3 2538.45   269.5 2542.73   285.7 2550.52   293.9 2551.85
   306.1 2556.88   318.3 2560.88   326.4  2562.8   347.9 2570.07   361.4 2573.68
#Mann= 3 ,-1,0
       0      .1       0   153.9    .045       0   164.8      .1       0
Bank Sta=153.9,164.8
XS Rating Curve= 0 ,0
Exp/Cntr(USF)=0,0
Exp/Cntr=0.3,0.1

Type RM Length L Ch R = 1 ,8094    ,89.8,86,83
XS GIS Cut Line= 3
2343969.13331616701459.5683256662343884.18956745701526.309842507
2343757.64071734701748.203716679
#Sta/Elev= 30
       0 2574.29    18.9 2568.35    31.7    2563    67.4 2549.62      73  2545.9
    80.3 2542.79    99.7 2532.76     108 2529.62   118.9 2526.47   129.7 2524.63
   142.4 2516.74   155.8 2513.18   166.6 2512.52   171.2 2512.55  173.812513.198
   180.5 2516.35     185 2517.72   198.8  2519.2   212.6 2518.41   221.8 2519.28
   233.6 2519.35   249.5 2521.07   263.3 2519.88   281.7    2521     292 2519.66
   304.7 2521.48   309.3 2522.91   313.9 2526.31   318.5 2528.65   363.5 2547.53
#Mann= 3 ,-1,0
       0      .1       0   155.8    .045       0  173.81      .1       0
Bank Sta=155.8,173.81
XS Rating Curve= 0 ,0
Exp/Cntr(USF)=0,0
Exp/Cntr=0.3,0.1

Type RM Length L Ch R = 1 ,8008    ,108.3,109,109.6
XS GIS Cut Line= 3
2343887.27142682701401.7834626012343780.36943015701492.313081403
2343748.20252304701750.033570676
#Sta/Elev= 30
       0 2570.56    10.3    2567    35.5 2556.15    84.1 2537.85   101.1 2532.02
   135.1 2523.21     145 2519.44   176.9 2515.39   193.4 2512.09  201.052508.055
   206.2 2507.28   214.6 2508.03   229.6 2513.34   233.7  2514.1   241.7  2514.6
   253.8 2514.43     270 2518.42   280.8 2518.12   294.1 2515.29   298.2 2515.02
   310.3 2516.38   318.3 2518.69   326.4 2521.96   338.5 2523.29   346.5 2528.02
   354.6  2531.8   362.7 2536.63   370.7 2539.06   382.8 2545.02   399.8 2550.65
#Mann= 3 ,-1,0
       0      .1       0  201.05    .045       0   214.6      .1       0
Bank Sta=201.05,214.6
XS Rating Curve= 0 ,0
Exp/Cntr(USF)=0,0
Exp/Cntr=0.3,0.1

Type RM Length L Ch R = 1 ,7899    ,130,134.7,139.4
XS GIS Cut Line= 3
2343793.85256486701329.5523837692343685.02440609701435.491299389
2343633.40326175701712.088177263
#Sta/Elev= 30
       0 2558.25     6.6 2556.48    24.7  2549.1    35.8 2546.21      47 2541.39
    74.9 2532.24   119.6  2520.2   128.2  2516.3   153.6 2508.08   169.9 2506.44
   182.1 2506.69   198.4 2503.85   215.8 2507.21   222.8 2507.56   230.9 2506.06
   243.1 2505.72   254.42501.414   263.5 2500.74   274.6  2501.3   279.7  2502.9
     296 2514.13   304.1 2516.53   311.8 2520.29   320.4 2522.04   332.6 2522.71
   361.1 2526.56   377.4 2529.79   414.7 2544.62   422.2 2548.38   433.2 2551.33
#Mann= 3 ,-1,0
       0      .1       0   254.4    .045       0   274.6      .1       0
Bank Sta=254.4,274.6
XS Rating Curve= 0 ,0
Exp/Cntr(USF)=0,0
Exp/Cntr=0.3,0.1

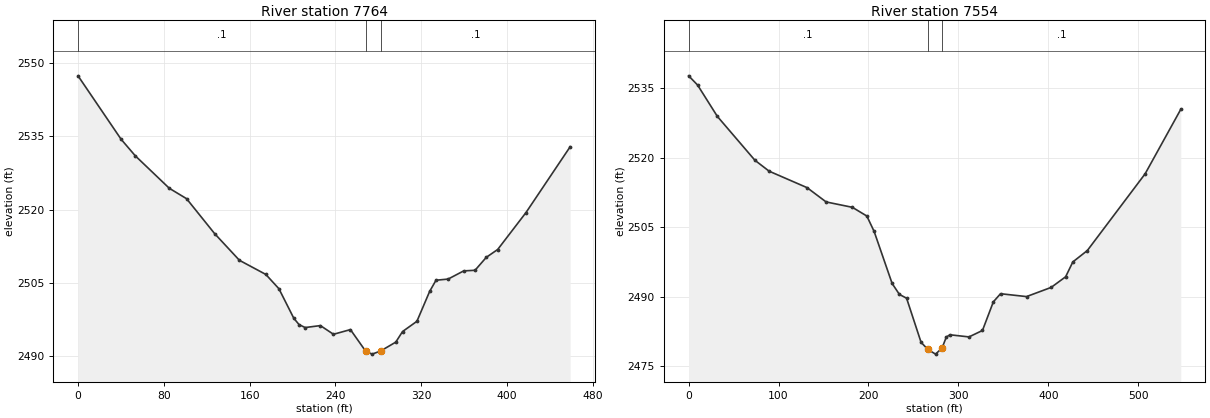
Type RM Length L Ch R = 1 ,7764    ,216,210.5,205.9
XS GIS Cut Line= 2
2343726.43689129701272.730601754 2343426.9186844701620.402861199
#Sta/Elev= 30
       0 2547.39    40.2  2534.4    53.4 2531.02    85.1 2524.38   101.2 2522.25
   127.3 2515.12   150.5 2509.64   175.1 2506.75   187.3 2503.83   201.2 2497.78
   206.1 2496.48   211.8 2495.88     226 2496.28   238.2  2494.5     254 2495.46
  268.162491.058   274.2 2490.44  282.112491.073   296.3  2492.9   302.6 2495.06
     316 2497.16   327.9 2503.29   333.8 2505.56   345.1  2505.8   359.6 2507.47
   370.2  2507.6   380.7 2510.25   391.3 2511.85   417.7 2519.41   458.9 2532.88
#Mann= 3 ,-1,0
       0      .1       0  268.16    .045       0  282.11      .1       0
Bank Sta=268.16,282.11
XS Rating Curve= 0 ,0
Exp/Cntr(USF)=0,0
Exp/Cntr=0.3,0.1

Type RM Length L Ch R = 1 ,7554    ,199.5,204.2,214.1
XS GIS Cut Line= 3
2343604.77815576  701181.23790192343444.90670128701236.133521813
2343408.30962134 701612.69821279
#Sta/Elev= 30
       0 2537.62     9.9 2535.64    31.9 2528.88    73.7 2519.42    89.5 2517.07
   131.7 2513.52   152.9 2510.44   182.1 2509.28   198.2  2507.4   206.3 2504.08
   226.3 2492.87   234.4 2490.51   242.4 2489.69   258.5 2480.19     2662478.662
   274.6 2477.64   281.82478.938   286.6 2481.32   290.6 2481.81   311.8 2481.35
   326.8 2482.74   338.9 2488.91   346.9 2490.66   375.8 2490.04   403.2 2492.02
   419.3 2494.31   427.3 2497.51   443.4 2499.96   507.7  2516.5   547.4 2530.41
#Mann= 3 ,-1,0
       0      .1       0     266    .045       0   281.8      .1       0
Bank Sta=266,281.8
XS Rating Curve= 0 ,0
Exp/Cntr(USF)=0,0
Exp/Cntr=0.3,0.1