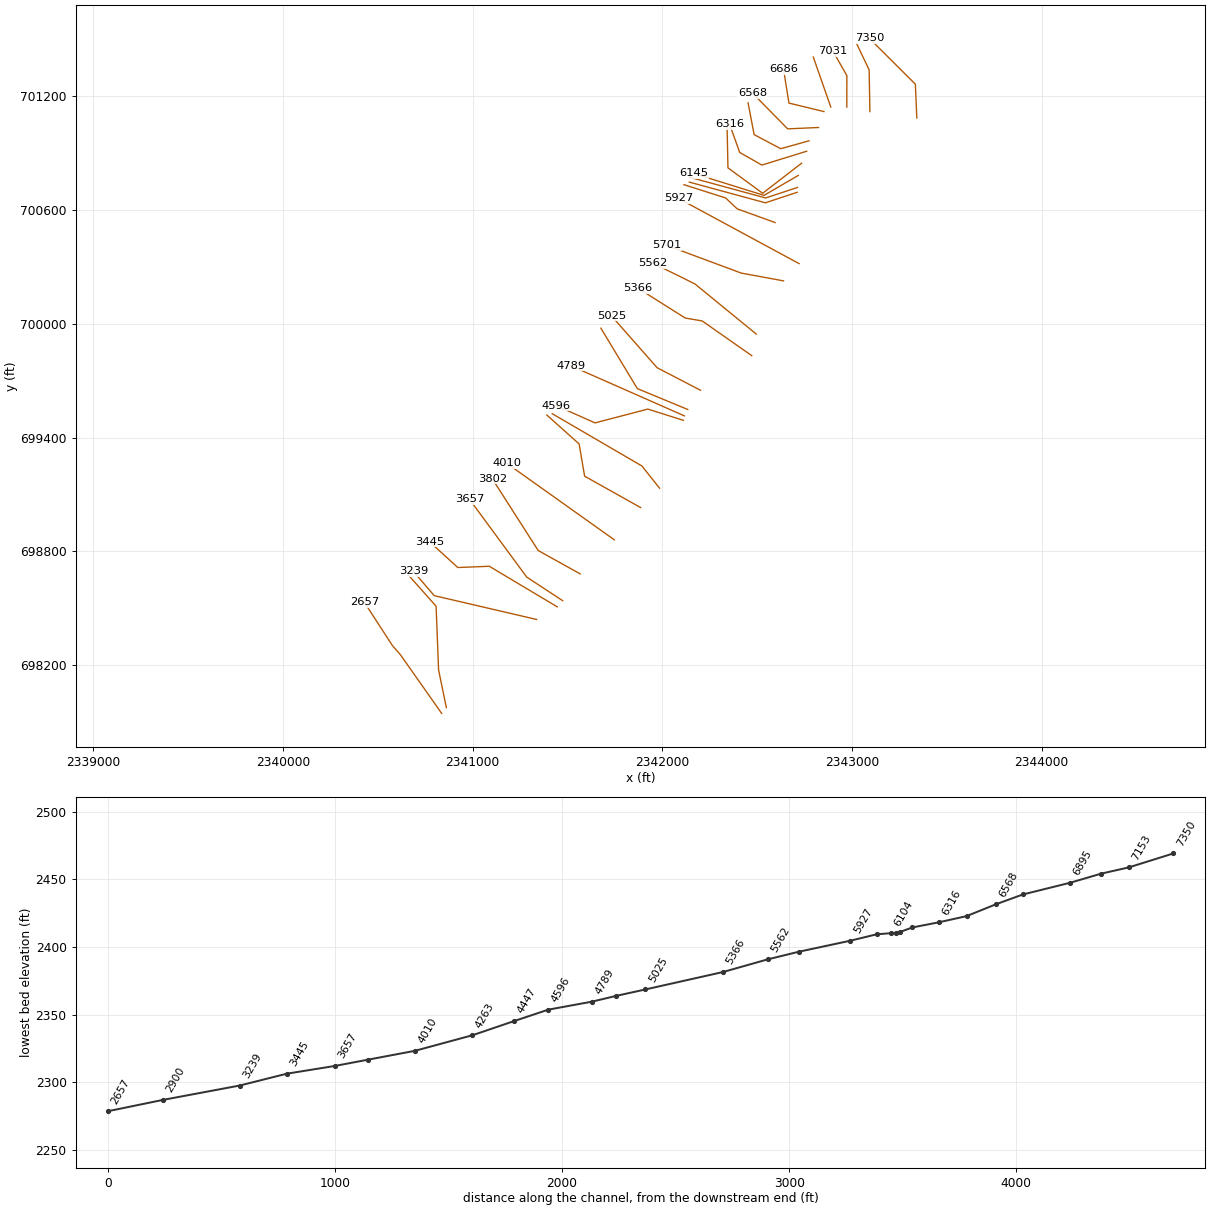
HEC-RAS study TAYLORRN.prj: TAYLORRN

--- TAYLORRN.g01 (geometry) --- (continued)

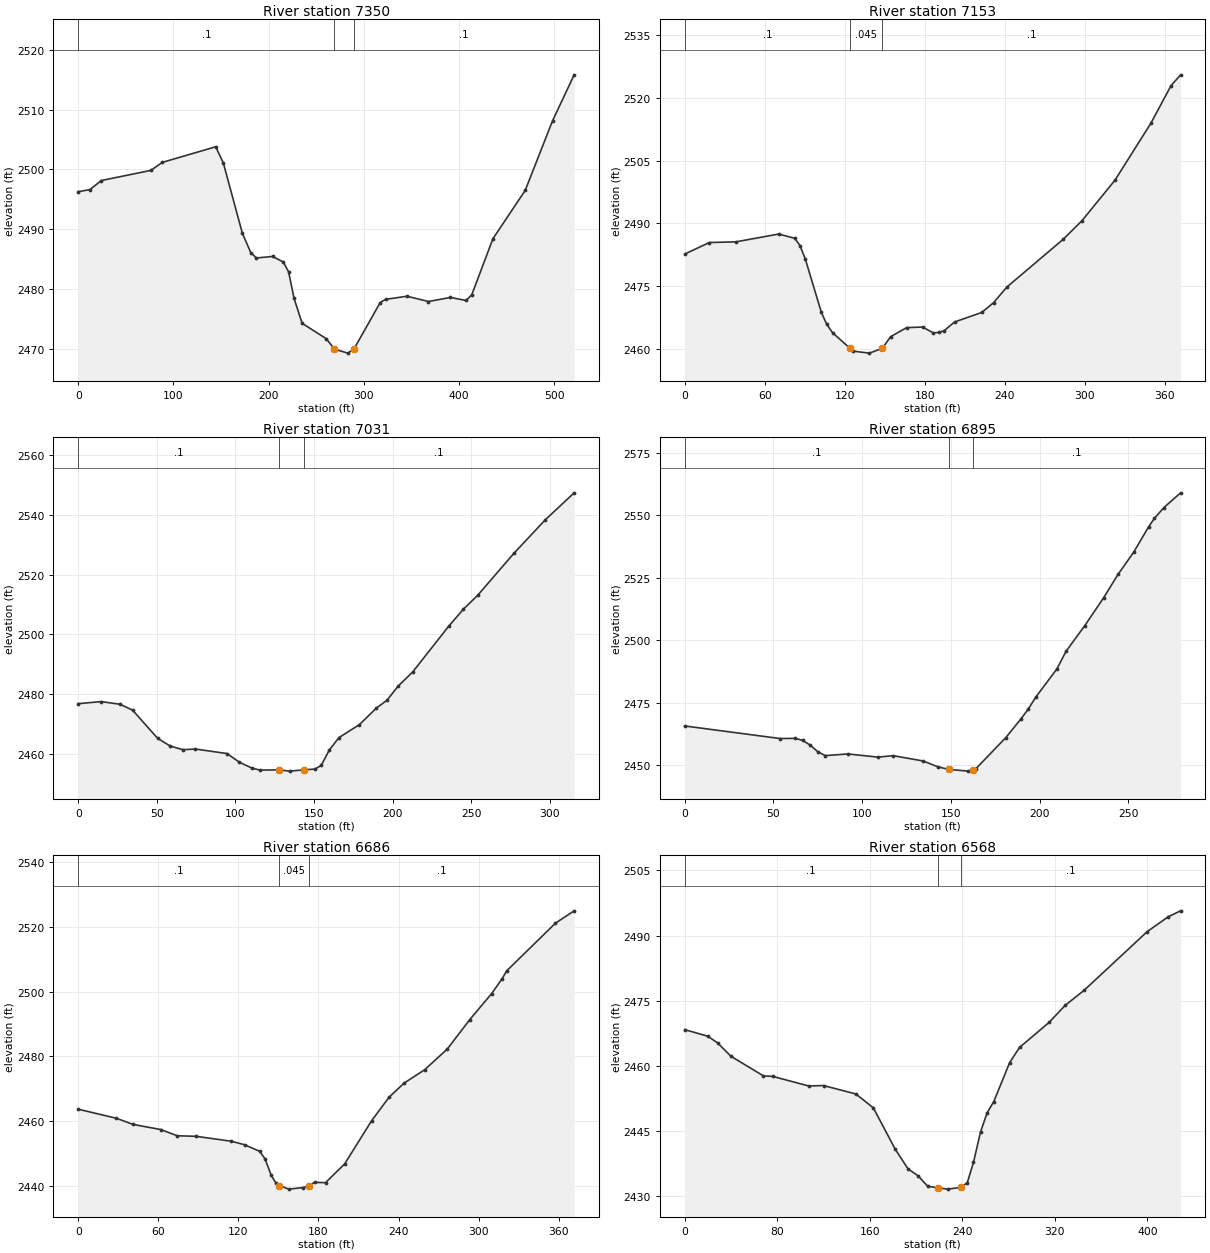
Type RM Length L Ch R = 1 ,7350    ,203.5,196.5,186.1
XS GIS Cut Line= 3
 2343342.1675519701084.9297967912343334.46290349701263.099791243
2343091.76647861701504.833135068
#Sta/Elev= 30
       0 2496.27    12.3 2496.62    24.3 2498.14    76.3 2499.83    88.3 2501.17
   144.4 2503.78   152.4 2501.09   172.4 2489.33   181.3 2486.07   187.2 2485.19
   204.1 2485.44   215.4 2484.52     221 2482.86   226.7 2478.43   235.2 2474.26
   260.6 2471.69   269.1 2469.95   283.2 2469.28  289.69 2469.98   317.2 2477.74
   322.8 2478.27   345.3 2478.79   367.9 2477.91     391 2478.59   407.4 2478.08
   413.4 2479.05   435.6 2488.41   469.5 2496.49   498.2 2508.12   520.9 2515.81
#Mann= 3 ,-1,0
       0      .1       0   269.1    .045       0  289.69      .1       0
Bank Sta=269.1,289.69
XS Rating Curve= 0 ,0
Exp/Cntr(USF)=0,0
Exp/Cntr=0.3,0.1

Type RM Length L Ch R = 1 ,7153    ,123.1,121.6,120.9
XS GIS Cut Line= 4
2343094.65572177701118.7139869572343094.49194623 701131.46551181
2343090.80339756701338.2201132292343025.31388609701475.940703535
#Sta/Elev= 30
       0 2482.63    18.5 2485.39    38.5 2485.56    70.5 2487.42    82.5 2486.41
    86.5 2484.66    90.5 2481.43   102.5 2468.71   106.5 2465.85     111  2463.8
  124.122460.064   126.5 2459.41   138.5 2458.94  148.182460.062   154.5 2462.88
   166.5 2465.04   178.5 2465.18   186.5 2463.77   190.5 2463.91   194.5 2464.28
   202.5  2466.4   222.8 2468.66   231.7 2471.01   241.7 2474.75   283.8 2486.13
   298.1 2490.64   322.8 2500.32   349.8 2513.98   364.8 2522.91     372  2525.5
#Mann= 3 ,-1,0
       0      .1       0  124.12    .045       0  148.18      .1       0
Bank Sta=124.12,148.18
XS Rating Curve= 0 ,0
Exp/Cntr(USF)=0,0
Exp/Cntr=0.3,0.1

Type RM Length L Ch R = 1 ,7031    ,135.6,136.8,140
XS GIS Cut Line= 3
2342973.00677169701142.5893204392342973.30750933701308.364600645
 2342899.1502684701438.380542542
#Sta/Elev= 30
       0 2476.86    14.6 2477.55    26.6 2476.66    34.6  2474.7    50.6 2465.24
    58.6 2462.69    66.6 2461.48    74.6  2461.7    94.6  2460.2   102.6 2457.28
   110.6 2455.31   115.6 2454.66   127.7 2454.74   134.6 2454.32   143.7 2454.75
   150.6 2455.01   154.6 2456.22   159.7 2461.34   165.8  2465.5   178.9 2469.87
   189.7 2475.39   196.5 2478.03   203.6 2482.78   212.8 2487.46   235.8 2502.81
     245  2508.4   254.2 2513.11   277.2 2527.11   297.2 2538.33   315.5 2547.31
#Mann= 3 ,-1,0
       0      .1       0   127.7    .045       0   143.7      .1       0
Bank Sta=127.7,143.7
XS Rating Curve= 0 ,0
Exp/Cntr(USF)=0,0
Exp/Cntr=0.3,0.1

Type RM Length L Ch R = 1 ,6895    ,199.7,208.4,218.4
XS GIS Cut Line= 2
 2342888.5699732701142.4099062352342796.27688923 701406.16173093
#Sta/Elev= 30
       0 2465.66    53.8 2460.62    62.3  2460.7    66.5 2459.87    70.7 2457.98
      75 2455.36    79.2 2453.79    91.9 2454.46   108.9 2453.18   117.4 2453.77
   134.3 2451.65   142.8 2449.26  148.712448.291   159.7 2447.58   162.6 2448.19
     164 2448.51   180.9 2460.99   189.4 2468.45   193.6 2472.45   197.9  2477.3
   209.7  2488.5   214.8 2495.48   225.4 2505.81     236 2516.95   244.2 2526.39
     253 2535.25   261.4 2545.41   264.6 2548.71   269.9 2553.04   279.4 2558.98
#Mann= 3 ,-1,0
       0      .1       0  148.71    .045       0   162.6      .1       0
Bank Sta=148.71,162.6
XS Rating Curve= 0 ,0
Exp/Cntr(USF)=0,0
Exp/Cntr=0.3,0.1

Type RM Length L Ch R = 1 ,6686    ,124.2,118.3,111.6
XS GIS Cut Line= 3
2342852.26412643701118.7064457392342667.96491216701163.370696766
2342639.21291656701343.042564344
#Sta/Elev= 30
       0 2463.63    28.6 2460.82    41.2 2458.91    61.8 2457.34    74.2 2455.41
    88.3 2455.24   114.8 2453.71   124.7 2452.63   135.9  2450.6     140 2448.26
   144.6 2443.18   148.3 2440.67  150.612440.014   157.8  2438.9   168.8  2439.4
     173    2440   177.1 2440.99   185.3  2440.9   199.6 2446.68   219.8 2460.03
   232.9 2467.33   244.1 2471.67   259.6 2475.84   276.5 2482.22   293.3  2491.3
   309.8 2499.41   317.5 2503.92   321.1 2506.45   357.6 2521.19   371.6    2525
#Mann= 3 ,0,0
       0      .1       0  150.61    .045       0     173      .1       0
Bank Sta=150.61,173
XS Rating Curve= 0 ,0
Exp/Cntr(USF)=0,0
Exp/Cntr=0.3,0.1

Type RM Length L Ch R = 1 ,6568    ,126.5,129.3,132.6
XS GIS Cut Line= 3
2342824.16675353 701034.786169392342661.23123049701027.446731415
2342474.80950592701216.804231173
#Sta/Elev= 30
       0 2468.36      20 2466.84    28.4 2465.32      40 2462.23    68.1 2457.71
    76.1  2457.6   107.3 2455.39   120.1 2455.49   148.1 2453.54   163.1 2450.37
     182 2440.86   193.1 2436.33   201.8 2434.72   210.2 2432.31   218.8 2431.99
   227.3 2431.66   238.5 2432.05   244.3 2433.11   249.7 2437.81   255.8 2444.81
   261.5 2449.21   267.2 2451.77     281 2460.78   289.5 2464.25     315    2470
   329.1 2473.97   345.2 2477.36   399.8 2490.88   418.1 2494.33   428.8 2495.69
#Mann= 3 ,-1,0
       0      .1       0   218.8    .045       0   238.5      .1       0
Bank Sta=218.8,238.5
XS Rating Curve= 0 ,0
Exp/Cntr(USF)=0,0
Exp/Cntr=0.3,0.1

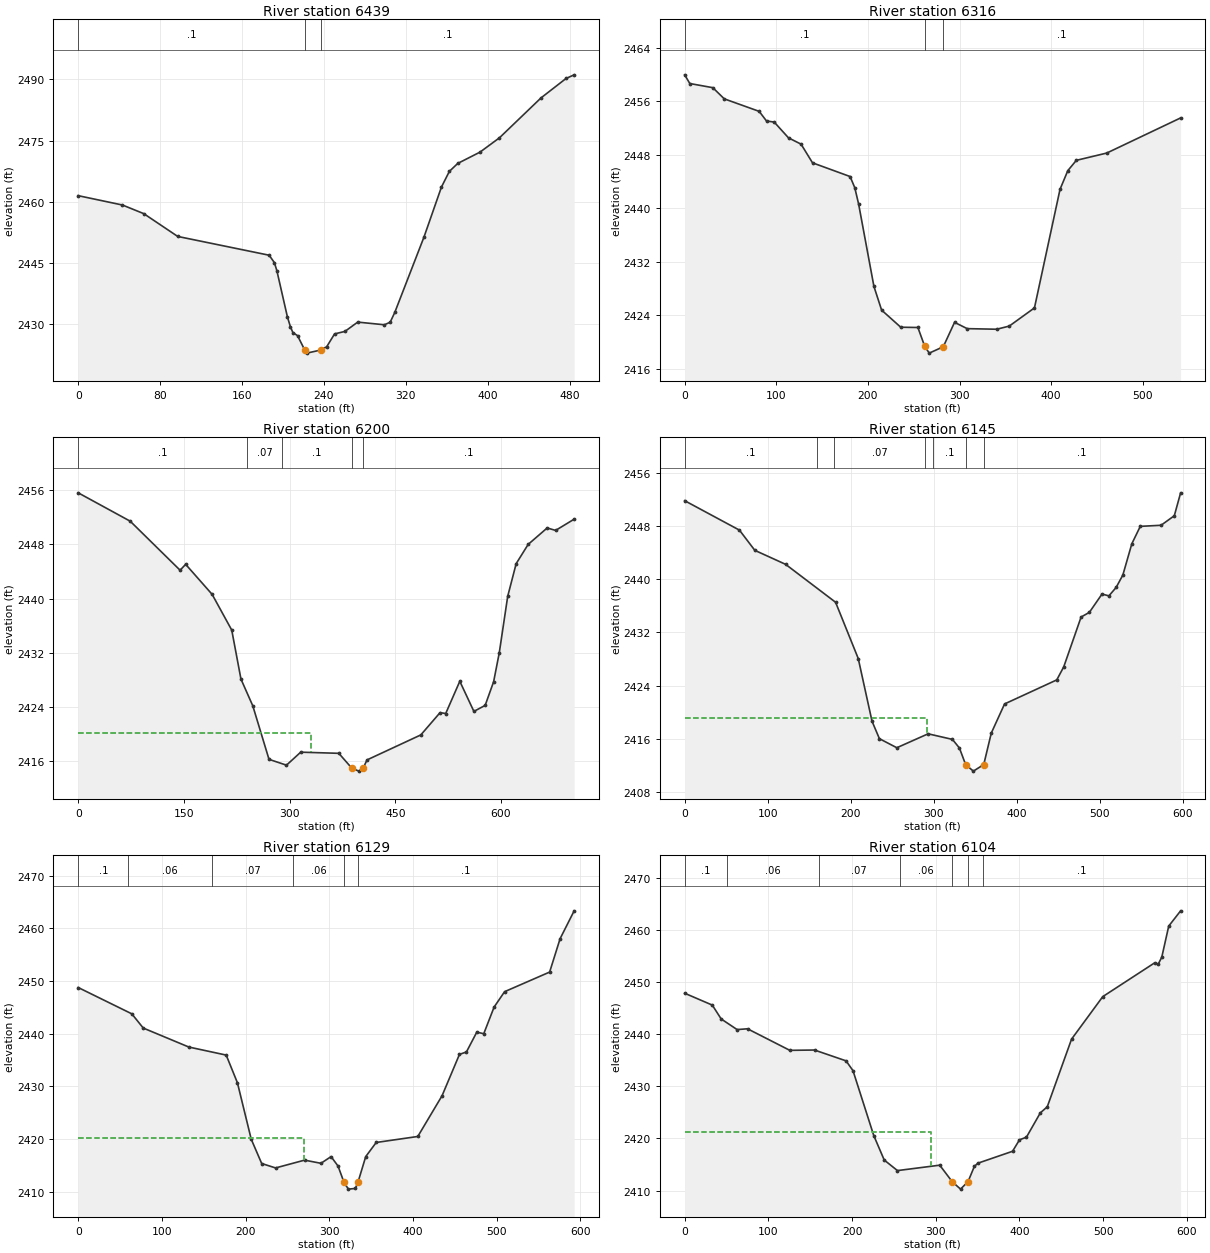
Type RM Length L Ch R = 1 ,6439    ,122.7,122.2,121.9
XS GIS Cut Line= 4
2342773.81838427700964.4480316242342624.61610197700922.879236555
2342484.32141861700997.109227749 2342452.4025224701164.869007848
#Sta/Elev= 30
       0 2461.49    43.2  2459.2      64 2457.09    97.2  2451.5   186.5  2446.9
   191.6 2445.09     194 2443.14   204.3 2431.82   207.2 2429.41   209.7 2427.93
   214.2  2427.2  221.342423.634   223.3 2422.91   236.9 2423.67   242.7 2424.47
   250.4 2427.62   260.5 2428.23     273 2430.51     299 2429.86   304.7 2430.48
   309.2 2432.88   337.7 2451.33   354.8 2463.61   362.5 2467.44   370.7 2469.39
   392.5 2472.17   411.4 2475.66   452.1 2485.46   476.5 2490.21   484.4  2491.1
#Mann= 3 ,-1,0
       0      .1       0  221.34    .045       0   236.9      .1       0
Bank Sta=221.34,236.9
XS Rating Curve= 0 ,0
Exp/Cntr(USF)=0,0
Exp/Cntr=0.3,0.1

Type RM Length L Ch R = 1 ,6316    ,118.4,116.3,115.3
XS GIS Cut Line= 4
2342761.48242859700909.5880174642342525.04639678 700836.52445305
2342408.35998134700902.9437797742342354.41302081701052.973307883
#Sta/Elev= 30
       0 2459.92     5.6 2458.62    30.7    2458    43.2 2456.33    81.3 2454.46
    89.3 2453.02    97.7 2452.86   113.3  2450.5     127 2449.56   139.5 2446.77
   180.5 2444.72   185.6 2443.06   189.8 2440.62   206.5 2428.31   214.9 2424.76
   235.8  2422.2   254.5 2422.16  261.922419.358   266.9 2418.33   282.22419.284
   294.5 2422.93   308.3 2421.99   340.5  2421.9   354.2 2422.37   381.7 2425.09
   409.6 2442.81   418.1  2445.6   427.4 2447.14   460.6 2448.23   541.2 2453.48
#Mann= 3 ,0,0
       0      .1       0  261.92    .045       0   282.2      .1       0
Bank Sta=261.92,282.2
XS Rating Curve= 0 ,0
Exp/Cntr(USF)=0,0
Exp/Cntr=0.3,0.1

Type RM Length L Ch R = 1 ,6200    ,52.1,54.5,57.2
XS GIS Cut Line= 4
2342734.56546669700846.4654110882342529.40628596700687.847257024
2342346.25363499700821.9264485312342341.79983552 701039.42032273
#Sta/Elev= 30
       0 2455.63    73.8 2451.44   144.6  2444.2   152.5 2445.07   190.1 2440.63
   217.9 2435.36     231 2428.12   247.8 2424.17   270.8 2416.27   295.6 2415.41
   315.8 2417.33   369.9 2417.16   388.62414.936   398.5 2414.53   404.6 2415.03
     410 2416.19   486.3 2419.88   513.6 2423.17   521.6 2423.04   541.6  2427.8
   561.6 2423.35   577.6 2424.24   589.6 2427.73   597.6 2431.99   609.6 2440.35
   621.6 2445.17   638.6 2448.01   665.6 2450.44   677.6 2450.08   703.9 2451.74
#Mann= 5 ,-1,0
       0      .1       0     240     .07       0  289.33      .1       0
   388.6    .045       0   404.6      .1       0
#XS Ineff= 2 , 0
          330.11 2420.17
Permanent Ineff=
       F       F
Bank Sta=388.6,404.6
XS Rating Curve= 0 ,0
Exp/Cntr(USF)=0,0
Exp/Cntr=0.3,0.1

Type RM Length L Ch R = 1 ,6145    ,15.6,16.4,17.3
XS GIS Cut Line= 3
2342717.22972743700782.0718932632342536.51972209700676.799791097
2342165.72324888 700792.30076149
#Sta/Elev= 30
       0 2451.77      66 2447.35    84.5 2444.32   121.6 2442.22   181.8 2436.53
   209.1 2428.09   225.7 2418.68   234.6 2416.06   255.6  2414.7   293.3 2416.79
   322.6 2415.95     331 2414.66   338.52412.165   347.8 2411.19   360.3 2412.17
   369.4  2416.9   385.4 2421.27   448.3 2424.88   456.7 2426.84   477.6 2434.31
   487.6 2435.02   502.8 2437.76   511.1 2437.49   519.8 2438.75   527.9 2440.61
   538.7  2445.3   548.9 2447.92   573.9 2448.08   589.9 2449.51   597.5 2452.95
#Mann= 7 ,-1,0
       0      .1       0     160     .06       0     180     .07       0
  289.14     .06       0  299.14      .1       0   338.5    .045       0
   360.3      .1       0
#XS Ineff= 2 , 0
          291.45 2419.15
Permanent Ineff=
       F       F
Bank Sta=338.5,360.3
XS Rating Curve= 0 ,0
Exp/Cntr(USF)=0,0
Exp/Cntr=0.3,0.1

Type RM Length L Ch R = 1 ,6129    ,25.3,25.2,25.1
XS GIS Cut Line= 3
  2342712.967699700718.5676696892342545.04377895700663.161300128
2342143.98690389700772.269227879
#Sta/Elev= 30
       0 2448.75      64 2443.76    77.7 2441.06   132.1 2437.46   176.8 2435.93
   190.2 2430.68   206.7 2419.97   219.2 2415.36   235.8 2414.52   270.4    2416
     290  2415.4   302.1 2416.67   310.4 2414.88   317.6 2411.76   322.8  2410.5
   331.1 2410.63  334.232411.807   343.5 2416.67     356 2419.35   405.7 2420.49
   434.7 2428.22   455.5 2436.07   463.8 2436.52   476.2 2440.29   484.5 2439.98
   496.9 2445.05   509.4 2447.96   563.2 2451.68   575.7 2458.01   592.5  2463.3
#Mann= 6 ,-1,0
       0      .1       0      60     .06       0     160     .07       0
  256.83     .06       0   317.6    .045       0  334.23      .1       0
#XS Ineff= 2 , 0
          269.89 2420.14
Permanent Ineff=
       F       F
Bank Sta=317.6,334.23
XS Rating Curve= 0 ,0
Exp/Cntr(USF)=0,0
Exp/Cntr=0.3,0.1

Type RM Length L Ch R = 1 ,6104    ,65.6,61.3,54
XS GIS Cut Line= 3
2342711.47598905700692.995499123  2342543.552069700637.589129562
2342142.49519394700746.697057313
#Sta/Elev= 30
       0  2447.9      33 2445.62    43.6 2442.96    62.6 2440.92    75.1 2441.07
   125.6 2436.93   155.1 2436.99   192.8 2434.91   201.1 2433.02   225.9 2420.56
   238.4 2415.86   254.2 2413.83   304.7 2414.87   319.72411.685   329.6 2410.27
  338.572411.725   346.1 2414.64   350.3 2415.25   391.7 2417.54     400 2419.74
   408.3 2420.25   424.9 2424.92   433.2 2426.09   462.2 2439.08   499.5 2447.25
   561.7 2453.76   565.8  2453.5     570 2454.83   578.3  2460.8   592.5 2463.73
#Mann= 7 ,-1,0
       0      .1       0      50     .06       0     160     .07       0
  256.83     .06       0   319.7    .045       0  338.57     .06       0
  356.83      .1       0
#XS Ineff= 2 , 0
          294.42 2421.28
Permanent Ineff=
       F       F
Bank Sta=319.7,338.57
XS Rating Curve= 0 ,0
Exp/Cntr(USF)=0,0
Exp/Cntr=0.3,0.1

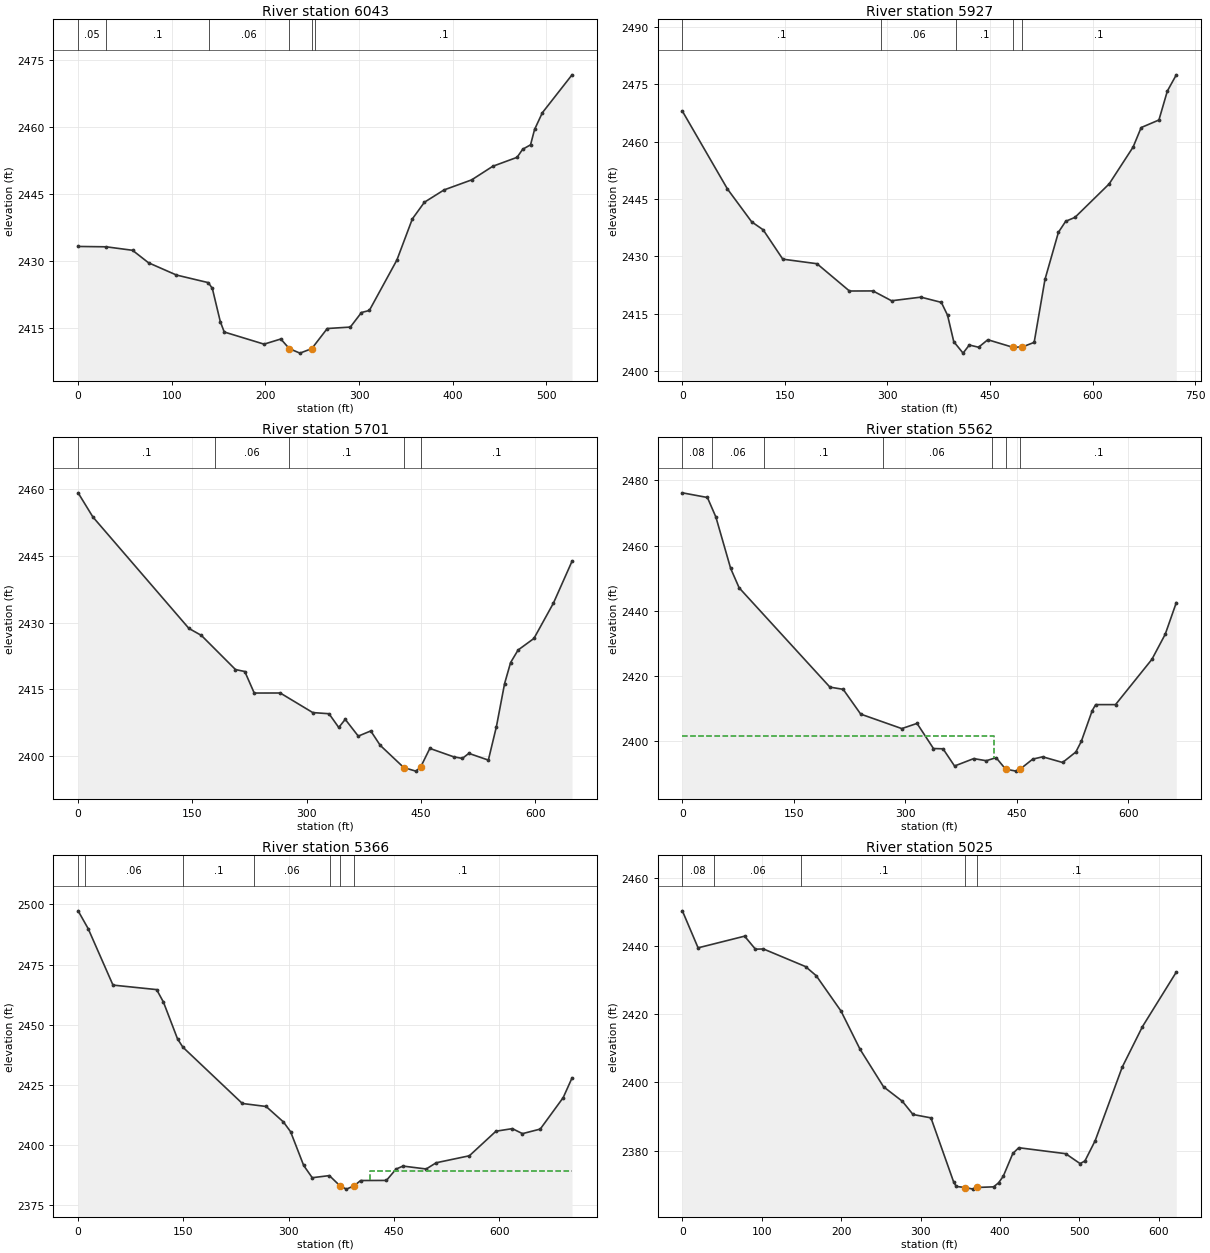
Type RM Length L Ch R = 1 ,6043    ,113.3,115.6,115.5
XS GIS Cut Line= 4
2342594.91794096700533.5461014152342394.81898044700605.775230348
 2342334.3768364700663.074267376 2342113.9765532  700733.2438981
#Sta/Elev= 30
       0 2433.34      30 2433.26    58.1 2432.48    75.2 2429.68     105 2426.94
     139 2425.24   143.3 2423.94   151.8 2416.51     156 2414.19   198.5 2411.47
   216.4 2412.62   225.5 2410.46   236.8 2409.46   249.4 2410.46     266 2414.97
   290.6 2415.29   302.5 2418.55   310.9 2419.01   340.3 2430.29   356.8  2439.5
   369.7 2443.24   390.7    2446   420.1 2448.24   442.7 2451.29   468.6 2453.29
   474.6  2455.1     483 2456.09   487.3 2459.53   495.6 2463.27   527.3 2471.76
#Mann= 6 ,-1,0
       0     .05       0      30      .1       0     140     .06       0
   225.5    .045       0   249.4     .06       0  252.74      .1       0
Bank Sta=225.5,249.4
XS Rating Curve= 0 ,0
Exp/Cntr(USF)=0,0
Exp/Cntr=0.3,0.1

Type RM Length L Ch R = 1 ,5927    ,224.7,226.2,226.4
XS GIS Cut Line= 2
2342721.41462188700316.9891354252342085.81929324 700660.47483266
#Sta/Elev= 30
       0 2467.96      66  2447.6   101.4 2439.03   118.2 2436.95   146.9 2429.28
   196.9 2428.09   244.4 2420.96   278.8 2420.98     306 2418.41   348.9 2419.36
   378.8 2417.99   387.9 2414.63     397 2407.72   410.6 2404.73   419.7 2406.85
   433.3 2406.27   446.8 2408.23   483.4 2406.26     497 2406.32   514.6 2407.54
   530.4 2423.98   550.1 2436.31   560.7 2439.17   574.3  2440.2   624.3 2448.94
   659.3 2458.56   671.1 2463.66   697.1 2465.64   709.4  2473.2   722.5 2477.44
#Mann= 5 ,-1,0
       0      .1       0     290     .06       0     400      .1       0
   483.4    .045       0     497      .1       0
Bank Sta=483.4,497
XS Rating Curve= 0 ,0
Exp/Cntr(USF)=0,0
Exp/Cntr=0.3,0.1

Type RM Length L Ch R = 1 ,5701    ,139.8,138.4,137.1
XS GIS Cut Line= 3
2342639.21291656700225.9801045332342416.09400212700267.080957194
2342021.23223906700413.869716696
#Sta/Elev= 30
       0 2459.15    19.4 2453.72   145.4 2428.67   161.7 2427.11   206.5 2419.43
   218.7 2418.99   231.1 2414.15   265.2 2414.16   307.9 2409.76   329.2  2409.5
     342 2406.41   350.5 2408.24   367.6 2404.47     384 2405.63   396.4  2402.4
   427.4 2397.39   443.1  2396.6   449.3 2397.46   461.5 2401.71   492.9 2399.81
   504.2 2399.46   512.7 2400.59   538.3 2399.08   548.9 2406.63   559.6 2416.28
   567.5 2421.01   577.3 2423.82   598.1 2426.42   623.7 2434.37   648.1 2443.78
#Mann= 5 ,-1,0
       0      .1       0     180     .06       0  276.87      .1       0
   427.4    .045       0   449.3      .1       0
Bank Sta=427.4,449.3
XS Rating Curve= 0 ,0
Exp/Cntr(USF)=0,0
Exp/Cntr=0.3,0.1

Type RM Length L Ch R = 1 ,5562    ,195.9,196.5,201.6
XS GIS Cut Line= 4
2342495.73128446699945.2613796292342173.59674448700208.651701042
2342116.65645979700237.5228313082341950.78804318 700318.81560326
#Sta/Elev= 30
       0 2476.22    33.7 2474.79    45.1  2468.8      65 2453.04    76.4  2447.1
   198.6 2416.65   216.4 2415.98     240 2408.38   295.3 2403.94   315.8 2405.53
   337.9 2397.83   350.8 2397.74   366.3 2392.47   392.1 2394.74     409 2394.09
   422.2 2395.03     435 2391.51   449.1  2390.9   454.72391.542   471.5 2394.58
   484.9 2395.29   511.7 2393.55   529.5 2396.76   536.9 2400.04   551.6 2409.48
   556.2 2411.29   582.9 2411.29   631.9 2425.18   649.8 2432.86   664.7 2442.56
#Mann= 7 ,-1,0
       0     .08       0      40     .06       0     110      .1       0
     270     .06       0  416.11      .1       0     435    .045       0
   454.7      .1       0
#XS Ineff= 2 , 0
          419.49 2401.72
Permanent Ineff=
       F       F
Bank Sta=435,454.7
XS Rating Curve= 0 ,0
Exp/Cntr(USF)=0,0
Exp/Cntr=0.3,0.1

Type RM Length L Ch R = 1 ,5366    ,347,341.1,332.6
XS GIS Cut Line= 4
2342471.86114171699831.5829025892342210.23878005700014.682937089
2342121.31497705700029.9420512142341872.33877416 700186.81673619
#Sta/Elev= 30
       0 2497.36    14.3 2489.96    49.7 2466.46   111.9 2464.58   121.6 2459.38
   141.7 2444.05   149.3 2440.62     234  2417.2   267.9 2415.95   292.6  2409.5
   302.8 2405.43   321.4 2391.41   333.6 2386.31     358 2387.19  373.192382.923
   382.3 2381.56   393.22382.928   402.6 2385.14   439.3 2385.18   453.1 2389.91
   462.9 2391.15     496 2389.94   510.2 2392.53   557.5 2395.44   595.4 2405.66
   618.7 2406.73   633.2 2404.65   658.5 2406.55   691.2 2419.64   703.8 2427.85
#Mann= 7 ,-1,0
       0      .1       0      10     .06       0     150      .1       0
     250     .06       0  359.33      .1       0  373.19    .045       0
   393.2      .1       0
#XS Ineff= 2 , 0
                          415.83          2389.2
Permanent Ineff=
       F       F
Bank Sta=373.19,393.2
XS Rating Curve= 0 ,0
Exp/Cntr(USF)=0,0
Exp/Cntr=0.3,0.1

Type RM Length L Ch R = 1 ,5025    ,131.9,129.7,127.5
XS GIS Cut Line= 3
2342201.78241325 699649.100279692341972.79194842699767.999174887
2341732.10082847700041.115058126
#Sta/Elev= 30
       0 2450.28    19.8 2439.43    78.4 2442.85      92 2439.04   102.1  2439.1
   155.1 2433.94   168.6 2431.26   199.8  2420.9   223.8 2409.69   253.4 2398.69
   277.1 2394.44   290.5 2390.57   313.1 2389.58   341.5  2370.9   344.9 2369.48
   356.22369.162   366.2 2368.69   371.6 2369.18     392 2369.36   398.2 2370.53
   404.1 2372.43   416.2 2379.14   423.7 2380.83   482.8 2379.08   500.9 2376.18
     507 2376.94     520 2382.93     554 2404.46   579.5 2416.34   622.1 2432.32
#Mann= 5 ,-1,0
       0     .08       0      40     .06       0     150      .1       0
   356.2    .045       0   371.6      .1       0
Bank Sta=356.2,371.6
XS Rating Curve= 0 ,0
Exp/Cntr(USF)=0,0
Exp/Cntr=0.3,0.1

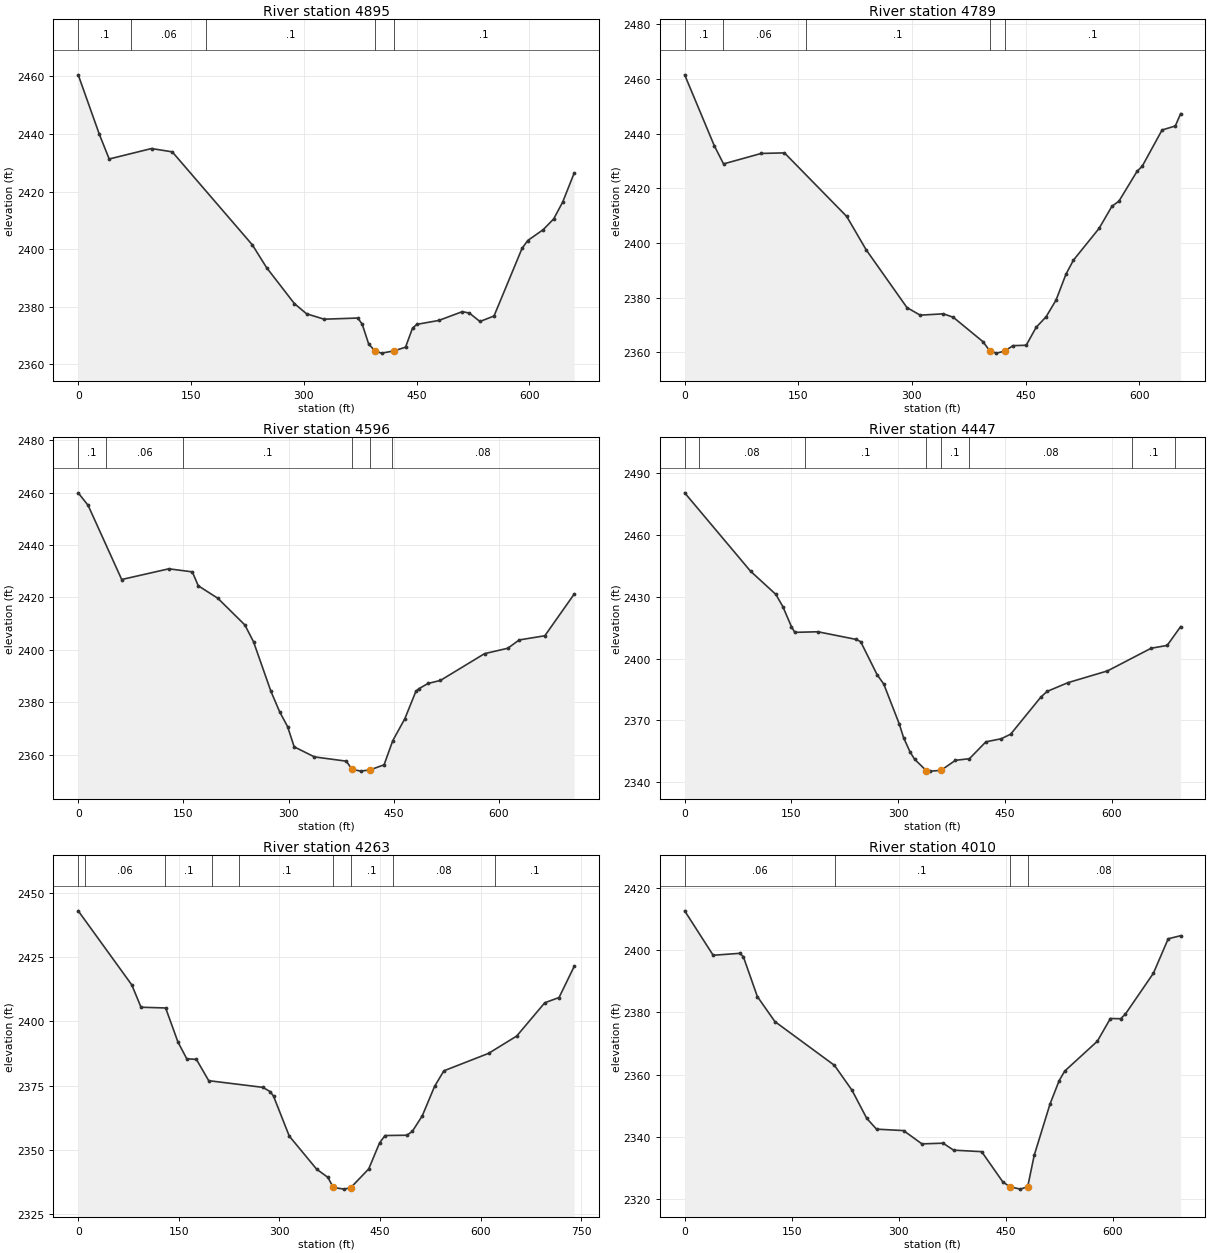
Type RM Length L Ch R = 1 ,4895    ,98.1,106,111.6
XS GIS Cut Line= 3
2342134.25958387699547.8160356342341868.57192918 699657.90760526
2341676.27865423 699976.43921338
#Sta/Elev= 30
       0 2460.58    28.2 2439.85    41.2 2431.34    97.5 2434.97   125.1 2433.82
   231.7 2401.48   250.6 2393.59   287.6 2381.09   303.8 2377.55   327.1 2375.68
   371.8 2376.08   377.7 2373.99   386.4 2367.05   395.2 2364.53   403.6 2363.89
   419.9 2364.66   435.4 2365.96   444.7 2372.57   450.5 2373.89   479.6 2375.24
     511 2378.31   520.4 2377.79   534.4 2374.88   553.1 2376.79   590.4 2400.29
     598 2403.02   618.5 2406.78   632.5 2410.53   644.4 2416.35   659.7 2426.43
#Mann= 5 ,-1,0
       0      .1       0      70     .06       0     170      .1       0
   395.2    .045       0   419.9      .1       0
Bank Sta=395.2,419.9
XS Rating Curve= 0 ,0
Exp/Cntr(USF)=0,0
Exp/Cntr=0.3,0.1

Type RM Length L Ch R = 1 ,4789    ,181.1,192.8,196.5
XS GIS Cut Line= 2
2342116.64493273699514.0546209482341517.74679397699778.274388052
#Sta/Elev= 30
       0 2461.47    39.1 2435.52    51.3 2428.88   101.1 2432.71   131.7 2432.91
   213.9 2409.65   239.3 2397.56   293.4 2376.31   310.9 2373.54   341.5 2374.03
   354.6 2372.76     394 2363.77   402.7 2360.46   411.5 2359.65  422.452360.388
   433.3 2362.39   450.8 2362.53   463.9 2369.09   477.1 2372.97   490.2 2379.07
   503.3 2388.55   513.1 2393.65     547  2405.3   563.9 2413.37   573.2 2415.25
   597.3 2426.26   603.8 2427.97   630.1 2441.28   647.6 2442.76   654.6 2447.27
#Mann= 5 ,-1,0
       0      .1       0      50     .06       0     160      .1       0
   402.7    .045       0  422.45      .1       0
Bank Sta=402.7,422.45
XS Rating Curve= 0 ,0
Exp/Cntr(USF)=0,0
Exp/Cntr=0.3,0.1

Type RM Length L Ch R = 1 ,4596    ,158.2,149.8,140.8
XS GIS Cut Line= 4
2342111.37141063699490.6348670152341923.69523617699549.781273347
2341645.35435013699477.1238577382341441.98446386 699567.73420311
#Sta/Elev= 30
       0 2459.92    14.1 2455.15      62 2426.84   129.2 2430.92   162.7 2429.76
   171.1 2424.47   199.2 2419.65   237.6  2409.5     250 2403.06   274.8 2384.14
   287.2 2376.36   298.5 2370.72   307.9 2362.99   336.8 2359.14   382.3 2357.51
   390.3 2354.41     403 2353.71   416.5 2354.22   436.1 2356.12   448.5 2365.35
   465.7 2373.71   481.5  2384.2   485.7 2385.17   498.9 2387.18   516.4 2388.32
   579.3 2398.54   612.4  2400.6   628.8 2403.78   665.3 2405.37   707.1 2421.26
#Mann= 6 ,-1,0
       0      .1       0      40     .06       0     150      .1       0
   390.3    .045       0   416.5      .1       0  446.78     .08       0
Bank Sta=390.3,416.5
XS Rating Curve= 0 ,0
Exp/Cntr(USF)=0,0
Exp/Cntr=0.3,0.1

Type RM Length L Ch R = 1 ,4447    ,193.4,183.6,173.5
XS GIS Cut Line= 3
2341985.64653609699132.8045453262341893.02262748699249.591212693
2341419.83526832 699525.44937527
#Sta/Elev= 30
       0 2480.47    92.5 2442.42   128.1 2431.14     138 2425.16     150 2415.47
   154.7  2412.7   187.1 2412.99   241.4 2409.24   247.3 2408.15   270.4 2392.12
   279.7  2387.6   301.5 2368.21   307.5 2361.62   316.7 2354.58     323  2351.1
   339.5 2345.53   345.3  2345.3     360 2345.65   380.4 2350.55   400.1 2351.34
   423.2 2359.53   444.8 2361.03     458 2363.25   500.4 2381.24   509.1    2384
   538.4 2388.26     594 2393.97   655.4 2404.99   677.9 2406.35   696.8 2415.49
#Mann= 8 ,-1,0
       0      .1       0      20     .08       0  169.06      .1       0
   339.5    .045       0     360      .1       0  399.06     .08       0
  629.06      .1       0  689.06     .08       0
Bank Sta=339.5,360
XS Rating Curve= 0 ,0
Exp/Cntr(USF)=0,0
Exp/Cntr=0.3,0.1

Type RM Length L Ch R = 1 ,4263    ,242.3,253,262.3
XS GIS Cut Line= 4
2341885.86329155699030.5602790672341590.54068442699196.119922462
 2341561.4558822699366.1541508142341391.42165385699518.290039339
#Sta/Elev= 30
       0 2442.97    79.9 2414.16    93.6  2405.5   130.3 2405.22   148.7 2391.95
   161.8 2385.47   176.2 2385.23   194.5 2376.96   275.3 2374.36   286.2 2372.69
   291.1 2370.95   314.6 2355.42   355.4 2342.56   372.1  2339.4   380.2 2335.45
   396.5 2334.81   406.32335.396     433 2342.67   449.2 2352.79   457.3 2355.64
   489.8 2355.76   497.9 2357.23   512.8 2363.28   531.1 2374.71     545 2380.79
   611.6 2387.57   653.6 2394.31   695.4 2407.24   716.7 2409.28   739.2 2421.35
#Mann= 9 ,-1,0
       0      .1       0      10     .06       0     130      .1       0
     200     .06       0     240      .1       0   380.2    .045       0
   406.3      .1       0  468.56     .08       0  621.07      .1       0
Bank Sta=380.2,406.3
XS Rating Curve= 0 ,0
Exp/Cntr(USF)=0,0
Exp/Cntr=0.3,0.1

Type RM Length L Ch R = 1 ,4010    ,212.3,208,203.2
XS GIS Cut Line= 2
 2341747.1511579698860.5260507152341181.11616088699263.238696811
#Sta/Elev= 30
       0 2412.57    39.9 2398.32    77.3 2398.94    82.2 2397.85   101.8 2385.07
   126.4 2377.04   209.8 2363.01   234.4 2355.02     255 2346.02   268.7 2342.54
   306.6 2342.08   332.3 2337.82     362 2338.04   376.7  2335.8     416 2335.32
   445.5 2325.66   455.42324.053   470.3  2323.3  480.512324.093   489.6 2334.14
   511.7 2350.56   524.6 2358.13   532.4 2361.18     578 2370.73   596.3 2378.03
   610.7 2377.96   617.3 2379.44   656.6 2392.56   677.3 2403.61   694.7 2404.59
#Mann= 4 ,-1,0
       0     .06       0     210      .1       0   455.4    .045       0
  480.51     .08       0
Bank Sta=455.4,480.51
XS Rating Curve= 0 ,0
Exp/Cntr(USF)=0,0
Exp/Cntr=0.3,0.1

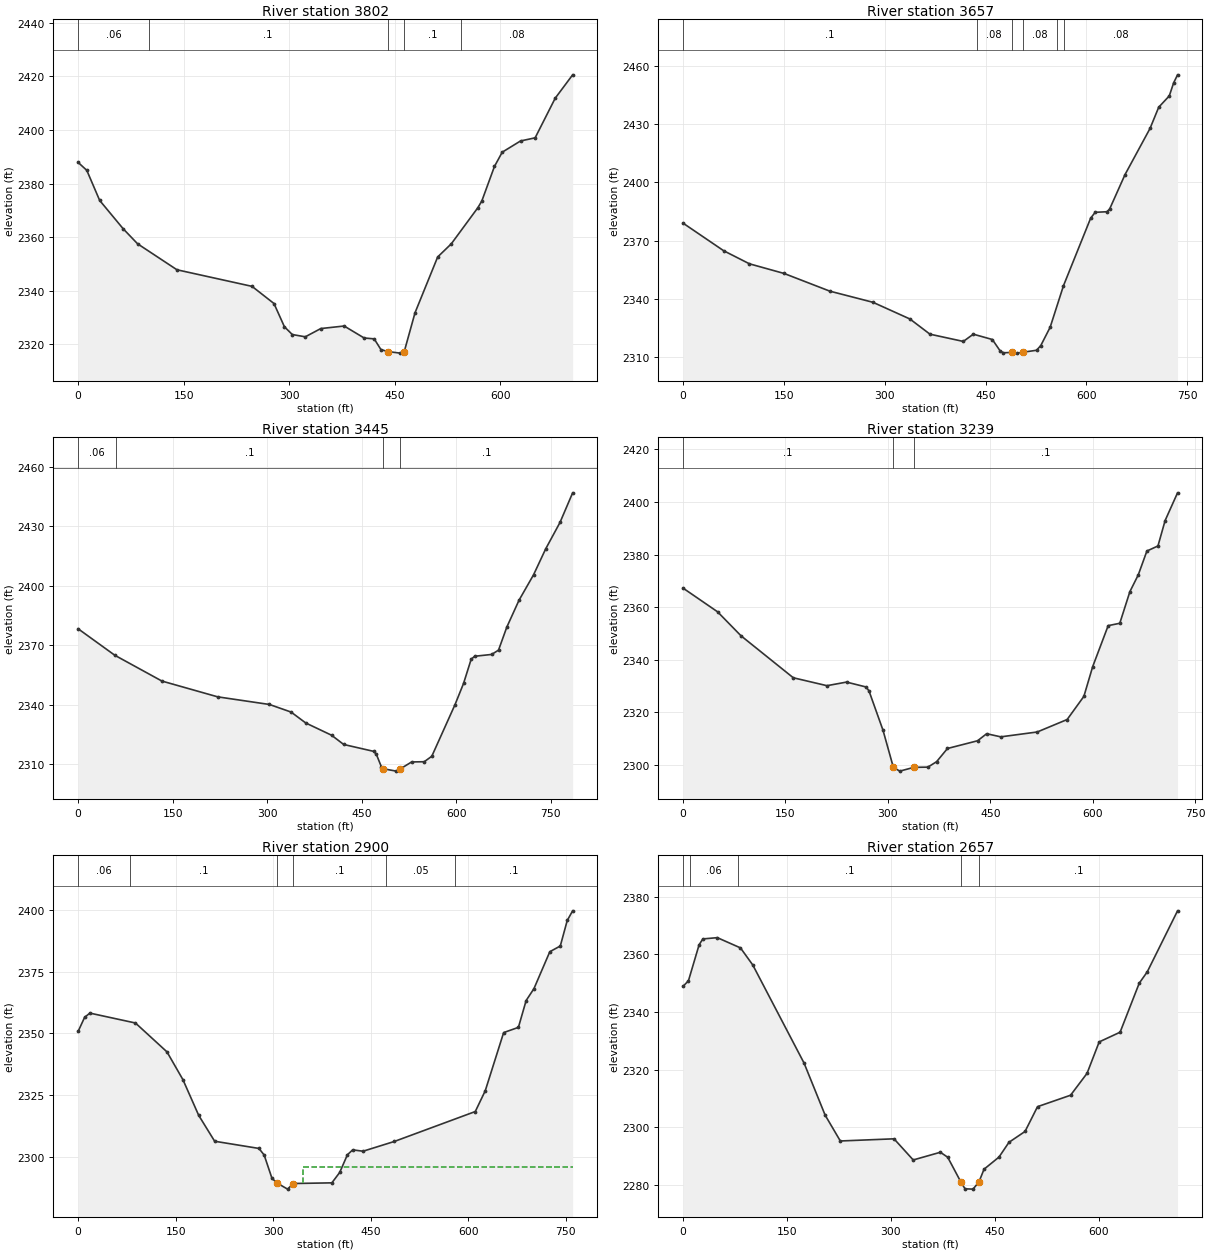
Type RM Length L Ch R = 1 ,3802    ,143.9,144.7,145.7
XS GIS Cut Line= 3
 2341566.9115743698680.9098557052341345.60083963698804.215993354
2341103.42064073699182.750219637
#Sta/Elev= 30
       0 2387.89    12.3 2384.93    30.6  2373.7      64 2363.12    84.5 2357.51
   140.4 2347.82   247.1 2341.63   278.3 2335.22   293.1 2326.56   304.3 2323.65
   322.8  2322.8   344.8 2325.88     378 2326.83   406.4 2322.36   420.7 2322.03
   430.2 2318.06   439.7  2317.3   457.8 2316.71   463.4 2317.28   478.7 2331.77
   510.9  2352.6   530.2 2357.49   567.9 2370.95   573.6 2373.47   591.6  2386.4
   602.6  2391.7   628.6 2395.89   649.4 2397.07   677.9 2411.85   702.7 2420.58
#Mann= 5 ,-1,0
       0     .06       0     100      .1       0   439.7    .045       0
   463.4      .1       0  543.34     .08       0
Bank Sta=439.7,463.4
XS Rating Curve= 0 ,0
Exp/Cntr(USF)=0,0
Exp/Cntr=0.3,0.1

Type RM Length L Ch R = 1 ,3657    ,199.3,212.1,222.3
XS GIS Cut Line= 3
2341474.78210733698539.6203611142341285.25434962698663.951178719
2340983.56440808699073.850008255
#Sta/Elev= 30
       0 2379.01    60.5 2364.79    98.8 2358.07   150.3 2353.11   218.4    2344
   282.5 2338.27   337.5 2329.68   367.3 2321.86   416.9 2318.13   431.8 2321.86
   460.1 2319.12   471.5 2313.36   476.5 2312.29   489.12312.469   496.4 2312.11
   505.2 2312.54   525.9 2313.59   532.2 2316.03   546.1 2325.43   565.9 2346.79
   606.4 2381.61   613.1 2384.58   630.5 2384.87   634.6 2386.29   657.5 2404.01
   694.7 2427.76   707.6 2438.67   723.3 2444.48   729.8  2451.2   735.6 2455.33
#Mann= 6 ,-1,0
       0      .1       0  436.67     .08       0   489.1    .045       0
   505.2     .08       0  556.67      .1       0  566.67     .08       0
Bank Sta=489.1,505.2
XS Rating Curve= 0 ,0
Exp/Cntr(USF)=0,0
Exp/Cntr=0.3,0.1

Type RM Length L Ch R = 1 ,3445    ,211.2,206.6,202.9
XS GIS Cut Line= 4
2341446.26110282 698507.00063678 2341087.9050174698721.035696303
2340921.54442329698714.5117514362340773.39762726698850.029031433
#Sta/Elev= 30
       0 2378.29    58.3 2364.89   132.9 2351.88   221.4  2343.9   303.6 2340.04
   337.9 2336.21   361.2 2330.69   402.1 2324.51   421.4 2319.83   469.2 2316.33
   473.2 2314.88   481.2 2308.52   483.9 2307.57   504.8 2306.36  511.17 2307.48
   529.2    2311   549.2 2311.11   561.2 2313.88   598.1 2340.01   611.6  2350.7
   623.7 2362.94   629.3 2364.41   656.2 2365.33   667.1 2367.52   680.2 2379.12
   699.6 2392.73   722.7  2405.6   741.9 2418.67   764.6 2432.02   784.7    2447
#Mann= 4 ,-1,0
       0     .06       0      60      .1       0   483.9    .045       0
  511.17      .1       0
Bank Sta=483.9,511.17
XS Rating Curve= 0 ,0
Exp/Cntr(USF)=0,0
Exp/Cntr=0.3,0.1

Type RM Length L Ch R = 1 ,3239    ,352.9,338.3,318.2
XS GIS Cut Line= 3
2341337.44590855698440.5060670322340797.58947082698566.092005717
2340686.68240809698694.939916836
#Sta/Elev= 30
       0 2367.25    50.6 2358.23    84.9 2349.11   161.5 2333.14   210.8 2330.13
   239.5  2331.5   268.2 2329.63   272.4 2328.12   292.9 2313.18   308.1 2299.03
   317.5 2297.63   338.1 2299.07   358.6 2299.15   371.4 2301.22   387.3 2306.24
   431.4 2309.18   444.7 2311.86   465.4 2310.67   518.8 2312.52   562.6 2317.26
   587.1 2326.06     600 2337.37   622.7 2352.97   639.7 2353.87   654.5 2365.91
   666.8  2372.3   679.4 2381.35   695.6 2383.28   706.1 2392.95   724.3 2403.49
#Mann= 3 ,-1,0
       0      .1       0   308.1    .045       0   338.1      .1       0
Bank Sta=308.1,338.1
XS Rating Curve= 0 ,0
Exp/Cntr(USF)=0,0
Exp/Cntr=0.3,0.1

Type RM Length L Ch R = 1 ,2900    ,236.6,242.8,253.4
XS GIS Cut Line= 4
 2340861.4283744 697975.426655812340820.42327786698174.655313712
2340807.37538812 698510.638474352340660.58662862698675.368082236
#Sta/Elev= 30
       0 2350.82      10 2356.53    18.1 2358.21    88.1 2354.21   136.6 2342.52
   161.1 2331.29   185.4 2316.82   209.9 2306.37     278 2303.46     286  2300.8
     298 2291.38     306 2289.44     322    2287   330.7 2289.27   390.1 2289.54
   402.1 2293.73     414 2300.91   422.1 2302.88   438.1 2302.34   486.1 2306.28
   610.6 2318.39   625.9 2326.78   654.2 2350.33   676.9 2352.44   688.8 2363.31
   700.8 2368.11   725.2 2383.05   741.3 2385.36     752 2395.71   760.3 2399.59
#Mann= 6 ,-1,0
       0     .06       0      80      .1       0     306    .045       0
   330.7      .1       0   473.4     .05       0  579.64      .1       0
#XS Ineff= 2 , 0
                          346.18         2296.08
Permanent Ineff=
       F       F
Bank Sta=306,330.7
XS Rating Curve= 0 ,0
Exp/Cntr(USF)=0,0
Exp/Cntr=0.3,0.1

Type RM Length L Ch R = 1 ,2657    ,158.3,152.7,140.9
XS GIS Cut Line= 4
2340836.64812291697945.3775805342340619.66441145698254.034633517
 2340576.5218243698303.7780897962340429.21702698698530.774106655
#Sta/Elev= 30
       0 2348.91     7.8 2350.84    23.2 2363.32    28.6 2365.35    49.5 2365.79
    82.9 2362.24   100.7  2356.3   174.7  2322.3   205.1 2304.26     227 2295.31
   304.5 2296.06   332.2 2288.73   371.4  2291.4     382 2289.67   401.32280.949
     407 2278.73   418.5 2278.62   427.12281.122   434.4 2285.52     456 2289.73
   470.4 2294.85   493.6 2298.61   511.6  2307.2   559.3 2311.17   583.1 2318.76
   600.6 2329.65   630.8 2333.02   658.4    2350     670 2353.94   713.7 2375.09
#Mann= 5 ,-1,0
       0      .1       0      10     .06       0      80      .1       0
   401.3    .045       0   427.1      .1       0
Bank Sta=401.3,427.1
XS Rating Curve= 0 ,0
Exp/Cntr(USF)=0,0
Exp/Cntr=0.3,0.1