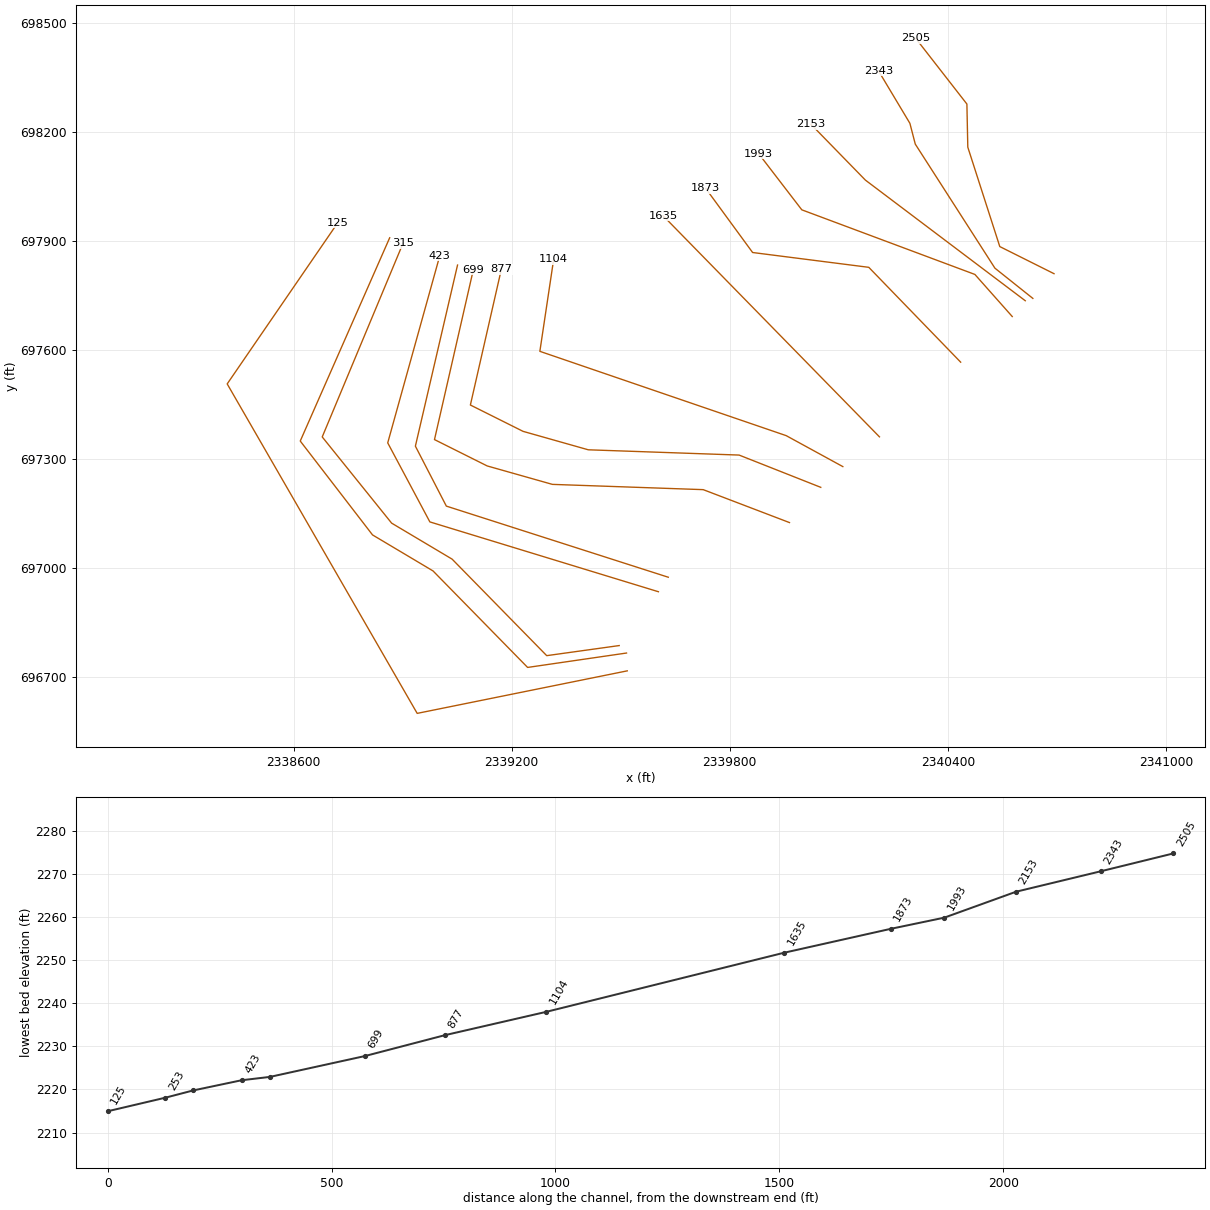
HEC-RAS study TAYLORRN.prj: TAYLORRN

--- TAYLORRN.g01 (geometry) --- (continued)

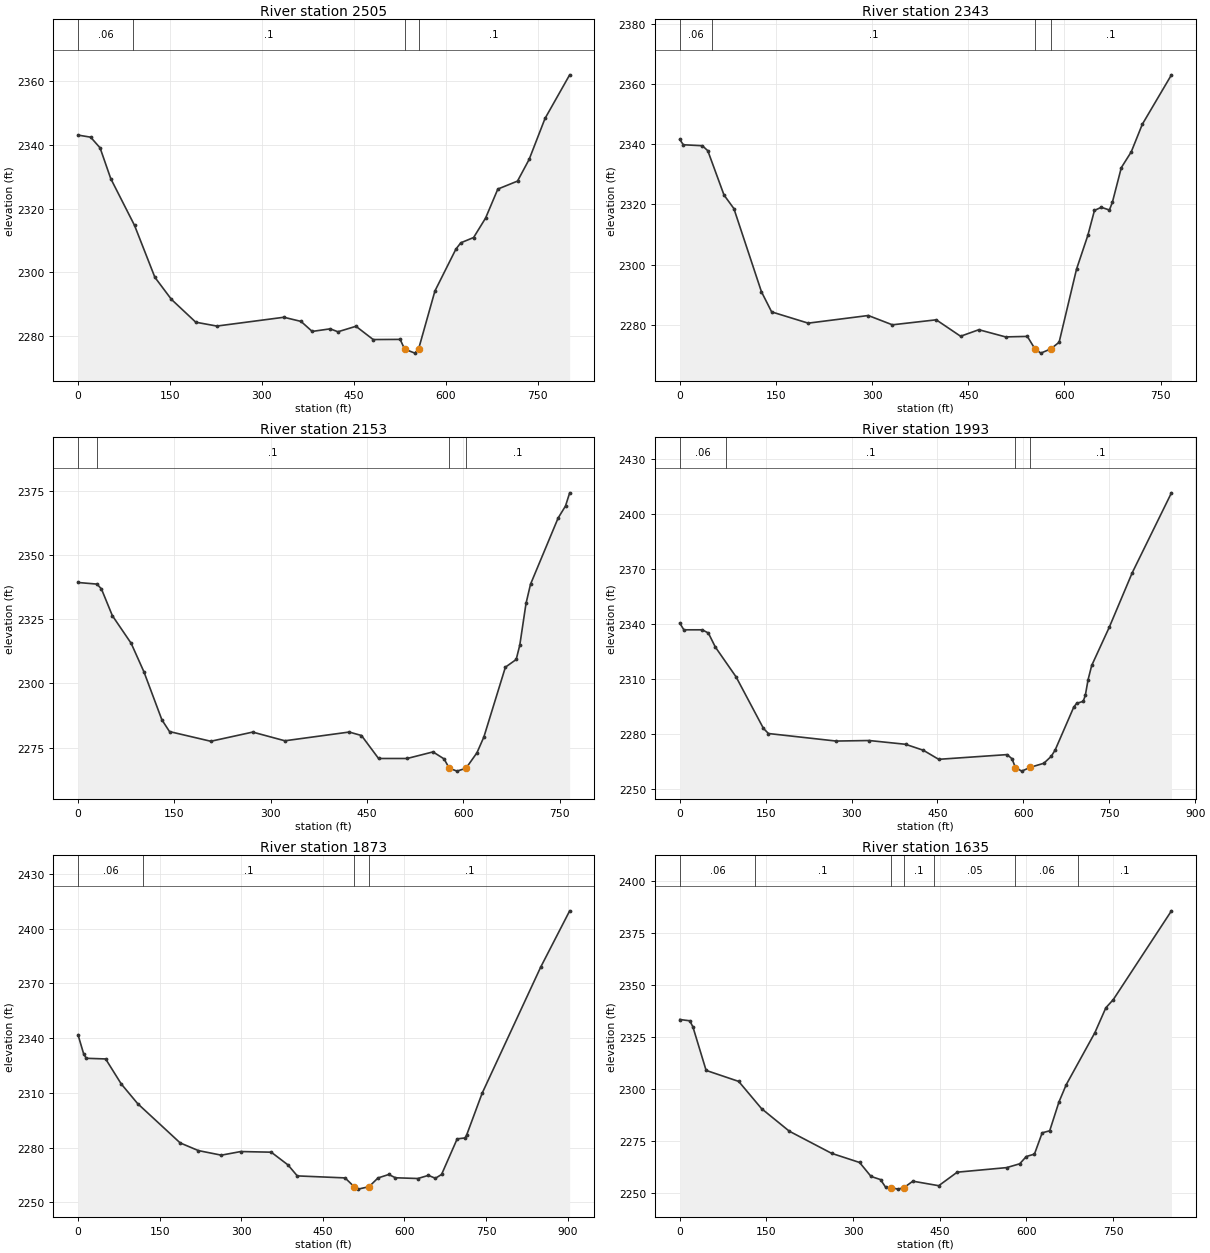
Type RM Length L Ch R = 1 ,2505    ,159.9,161.4,164.9
XS GIS Cut Line= 5
2340692.36960557697809.7327748672340543.15562102697884.339767141
 2340455.1572803698157.8583640442340452.63684426698276.592387828
2340311.82852793698457.337218347
#Sta/Elev= 30
       0 2343.11    20.6 2342.45      36  2339.1    53.4 2329.46    92.2 2314.78
   125.4 2298.49   152.3 2291.58   192.1  2284.4   226.5 2283.19   335.8 2285.95
   363.8 2284.65     382 2281.51   411.4 2282.32     424  2281.4   453.4 2283.12
   481.5 2278.96   525.5 2279.01  532.752275.961   549.5  2274.7  555.55 2275.99
   582.2  2294.2   616.4 2307.33   624.4 2309.31   645.3 2310.97   664.8 2317.06
   684.8 2326.17   716.9 2328.67   735.9 2335.49   761.8 2348.33     802 2362.01
#Mann= 4 ,-1,0
       0     .06       0      90      .1       0  532.75    .045       0
  555.55      .1       0
Bank Sta=532.75,555.55
XS Rating Curve= 0 ,0
Exp/Cntr(USF)=0,0
Exp/Cntr=0.3,0.1

Type RM Length L Ch R = 1 ,2343    ,182.4,190.1,195.7
XS GIS Cut Line= 5
2340634.14562486697741.7535176842340529.76250699697824.933814735
2340310.62757955698166.2629336542340295.78293454698223.570167893
 2340209.1800089698368.276937599
#Sta/Elev= 30
       0 2341.58     5.5 2339.82    35.2  2339.5    43.7 2337.84      69 2323.11
    84.4 2318.61   127.4 2290.96   143.3 2284.28   200.3 2280.54     294 2283.08
   331.6 2279.99     400 2281.65     438 2276.19   466.5 2278.36   508.2 2275.97
   542.1 2276.14  553.882272.025   563.2 2270.58   578.9 2272.01   591.7 2274.21
   618.8 2298.46   636.5 2309.73   646.8    2318   657.5 2319.04   670.1 2318.14
   674.7 2320.66   688.7 2332.22   704.2 2337.47   721.4 2346.61   766.9 2363.06
#Mann= 4 ,-1,0
       0     .06       0      50      .1       0  553.88    .045       0
   578.9      .1       0
Bank Sta=553.88,578.9
XS Rating Curve= 0 ,0
Exp/Cntr(USF)=0,0
Exp/Cntr=0.3,0.1

Type RM Length L Ch R = 1 ,2153    ,154.4,160.3,165.9
XS GIS Cut Line= 3
2340613.28802834697735.3247081142340173.27420766698067.318803825
2340023.62128492698220.823105791
#Sta/Elev= 30
       0 2339.23    29.6  2338.6    36.5 2336.71    53.5 2326.32    82.8 2315.55
   102.7 2304.44   130.6  2285.8   142.5 2281.21   206.8 2277.44     272 2281.01
   322.1 2277.63   422.3 2281.03   441.4 2279.68     468 2270.74   512.5 2270.74
   552.8  2273.3     570 2270.58  578.032266.982   590.1 2265.82   604.2 2266.95
   621.2 2272.96     632 2279.11   665.5 2306.27   682.3 2309.26   687.9 2314.82
   697.6 2331.06   704.6 2338.53   747.6 2364.31   759.1    2369   765.6 2374.12
#Mann= 4 ,-1,0
       0     .06       0      30      .1       0  578.03    .045       0
   604.2      .1       0
Bank Sta=578.03,604.2
XS Rating Curve= 0 ,0
Exp/Cntr(USF)=0,0
Exp/Cntr=0.3,0.1

Type RM Length L Ch R = 1 ,1993    ,117.4,119.9,123.6
XS GIS Cut Line= 4
2340577.40633157697691.8833935722340474.65419992697807.683414957
2339998.40622465697985.4609125762339879.34423083698140.404603161
#Sta/Elev= 30
       0 2340.53     7.1 2336.87    39.2 2336.87    49.9 2335.13    62.1 2327.47
    98.3 2311.21   146.1 2283.11   154.8 2280.32   272.9 2276.21   330.7  2276.5
   394.2 2274.45   425.3 2271.19   452.1 2266.25   571.6 2268.82   580.2 2266.54
   586.12261.757   597.2 2259.81  611.992261.876   635.7 2264.09   648.5 2267.83
   655.4 2271.25     688 2294.72     693 2296.74   704.5 2297.89   708.2 2301.17
     713 2309.65   719.3 2317.41   750.1 2338.34   790.1 2367.99   858.6 2411.57
#Mann= 4 ,-1,0
       0     .06       0      80      .1       0   586.1    .045       0
  611.99      .1       0
Bank Sta=586.1,611.99
XS Rating Curve= 0 ,0
Exp/Cntr(USF)=0,0
Exp/Cntr=0.3,0.1

Type RM Length L Ch R = 1 ,1873    ,243.3,238.2,227.4
XS GIS Cut Line= 4
2340435.51053072697566.2974548862340182.70766713697827.255249557
2339863.03436866697868.0299049742339734.18645754698044.176416377
#Sta/Elev= 30
       0 2341.82    10.5 2331.27    15.2 2328.92    50.8 2328.56    79.5 2314.86
   109.8 2304.03   187.8 2282.54   221.2 2278.34   263.5 2275.82   299.2 2277.81
   355.2 2277.46     386 2270.48   403.1 2264.46   490.9 2263.36   507.3 2258.63
   515.1 2257.21     535 2258.56   551.4 2263.32   571.2 2265.23   583.6 2263.43
   624.8 2263.03   644.1 2264.75     657 2263.16   668.3 2265.25     697 2284.75
   711.4 2285.27   714.2  2286.7   742.8 2309.71   850.6 2378.94   903.8 2409.74
#Mann= 4 ,-1,0
       0     .06       0     120      .1       0   507.3    .045       0
     535      .1       0
Bank Sta=507.3,535
XS Rating Curve= 0 ,0
Exp/Cntr(USF)=0,0
Exp/Cntr=0.3,0.1

Type RM Length L Ch R = 1 ,1635    ,521.2,530.4,534.8
XS GIS Cut Line= 2
2340212.06541903697360.7931915832339616.75544994697969.151050409
#Sta/Elev= 30
       0 2333.35    17.3 2332.73    22.7 2329.82    45.6 2308.84     102 2303.54
   141.6 2290.42   189.7 2279.55   262.9  2268.9   311.3  2264.5   331.1 2257.78
   347.5 2256.27   356.6 2252.48   365.9 2252.41   377.3 2251.67   387.7 2252.31
   403.5  2255.5   448.3 2253.32   480.3 2259.83   565.9 2262.03   588.5 2263.87
   599.9 2267.38     614 2268.53   627.4 2278.78   640.4 2279.77   656.4 2293.62
     669 2301.95   718.7 2327.04   737.6 2338.99   750.5 2342.93   851.2 2385.68
#Mann= 7 ,-1,0
       0     .06       0     130      .1       0   365.9    .045       0
   387.7      .1       0     440     .05       0     580     .06       0
     690      .1       0
Bank Sta=365.9,387.7
XS Rating Curve= 0 ,0
Exp/Cntr(USF)=0,0
Exp/Cntr=0.3,0.1

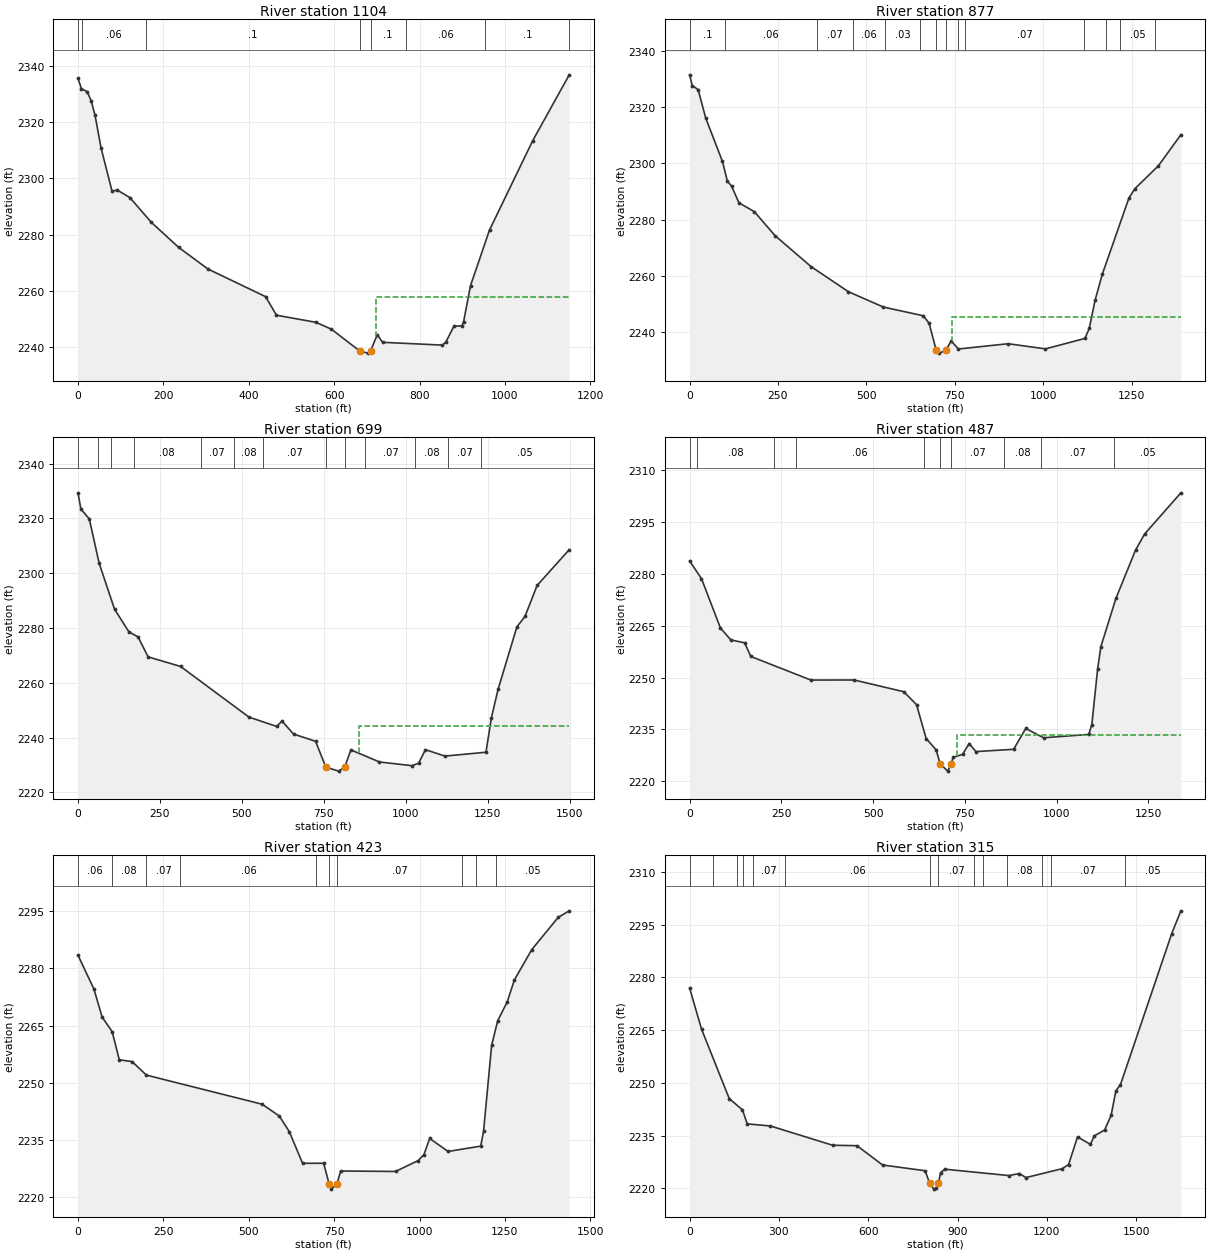
Type RM Length L Ch R = 1 ,1104    ,223.6,227.3,225.7
BEGIN DESCRIPTION:
Structure 2 XS 4
END DESCRIPTION:
XS GIS Cut Line= 4
2340111.26240812697278.9642166812339955.41261408 697364.13794133
 2339277.6472307697596.1004254822339315.70357575697849.809392522
#Sta/Elev= 30
       0 2335.47     8.1 2331.83    21.6 2330.77    30.9 2327.51      40 2322.35
      54 2310.82    79.7 2295.49    92.3 2295.82   121.4 2293.19   171.9 2284.38
     236 2275.48   304.4 2267.83   439.3 2258.04   464.9 2251.44   557.3 2248.92
   593.6 2246.48   659.7 2238.75   678.6 2237.99  685.192238.795     701 2244.51
   713.3 2241.83   853.2 2240.84   861.3 2241.84   880.2 2247.49   899.1 2247.71
   903.1 2249.14   919.3 2261.94   963.8 2281.67  1064.9 2313.36  1150.5 2336.74
#Mann= 8 ,-1,0
       0      .1       0      10     .06       0     160      .1       0
   659.7    .045       0  685.19      .1       0  767.61     .06       0
  953.97      .1       0 1150.51     .05       0
#XS Ineff= 2 , 0
                          698.34         2258.07
Permanent Ineff=
       F       F
Bank Sta=659.7,685.19
XS Rating Curve= 0 ,0
Exp/Cntr(USF)=0,0
Exp/Cntr=0.3,0.1

Type RM Length L Ch R = 1 ,877     ,172.6,177.9,195.4
BEGIN DESCRIPTION:
Structure 2 XS 3
END DESCRIPTION:
XS GIS Cut Line= 6
2340050.55347672697221.879699097 2339825.8398202697310.677837561
2339410.84443839 697325.175492822339231.43595456697375.917286229
2339086.45940196697448.4055625262339171.63312661697821.720185457
#Sta/Elev= 30
       0 2331.42     7.5 2327.59    24.1 2326.18    45.6 2316.06    92.9 2300.67
   106.9 2293.65   118.7 2291.89   139.6 2285.95   183.1 2282.82   241.6  2274.3
   343.4 2263.31   449.4 2254.36   548.2 2248.92   660.8 2245.84   677.4 2243.18
  697.382233.635   706.5 2232.56  724.932233.556   739.7 2236.86   760.4 2234.03
   900.9  2235.9  1006.5 2234.07  1118.1 2237.78  1130.4 2241.36  1146.8 2251.34
  1167.3  2260.6  1242.4  2287.6  1259.1 2290.94    1326 2299.11  1389.4 2310.13
#Mann= 14 ,-1,0
       0      .1       0     100     .06       0  361.62     .07       0
  462.21     .06       0  552.21     .03       0  652.21     .07       0
  697.38    .045       0  724.93     .07       0  757.99     .08       0
  777.99     .07       0 1116.52     .05       0 1176.52      .1       0
 1216.52     .05       0 1316.52      .1       0
#XS Ineff= 2 , 0
                          740.94         2245.24
Permanent Ineff=
       F       F
Bank Sta=697.38,724.93
XS Rating Curve= 0 ,0
Exp/Cntr(USF)=0,0
Exp/Cntr=0.3,0.1

Type RM Length L Ch R = 1 ,699     ,233,212.4,190.2
BEGIN DESCRIPTION:
Structure 2 XS 2
END DESCRIPTION:
XS GIS Cut Line= 6
2339964.47364861697124.9266295492339727.07454374697215.536974921
2339312.07916194 697230.03463018 2339132.6706781697280.776423588
2338987.69412551697353.2646998862339094.61433305697820.814082003
#Sta/Elev= 30
       0 2329.34     8.9 2323.42    34.6  2319.8    64.5 2303.67   111.6 2286.84
   155.4 2278.57   183.3 2276.75   213.8 2269.46   313.1 2265.95   521.7 2247.45
   606.1 2244.06   622.2 2246.01     658 2241.25   724.8 2238.64  756.092229.186
   795.1 2227.74  813.632229.189   832.5 2235.49   919.7 2231.08    1019 2229.73
  1039.1 2230.62    1060 2235.57  1119.5 2233.23  1244.6 2234.64    1261 2247.14
  1281.5 2257.58    1339 2280.43  1363.6 2284.21  1400.5 2295.51  1498.6  2308.6
#Mann= 13 ,-1,0
       0      .1       0      60     .07       0     100     .06       0
     170     .08       0   374.1     .07       0  474.69     .08       0
  564.69     .07       0  756.09    .045       0  813.63     .08       0
  876.92     .07       0 1029.01     .08       0 1129.01     .07       0
 1229.01     .05       0
#XS Ineff= 2 , 0
                          858.34         2244.21
Permanent Ineff=
       F       F
Bank Sta=756.09,813.63
XS Rating Curve= 0 ,0
Exp/Cntr(USF)=0,0
Exp/Cntr=0.3,0.1

Type RM Length L Ch R = 1 ,487     ,64,63.5,62.6
BEGIN DESCRIPTION:
Structure 2 XS 1
END DESCRIPTION:
XS GIS Cut Line= 4
2339631.02757765696974.5134562322339020.31384984697170.231802235
2338935.14012519697335.1426308112339051.12136727697833.499530355
#Sta/Elev= 30
       0 2283.79    32.4 2278.65    83.9  2264.4   112.2 2260.91     150 2260.07
   166.8 2256.11   330.6 2249.28   448.2  2249.3   583.3 2245.91   618.3 2242.18
   644.6 2232.33   671.6 2229.08682.72642225.043   703.2  2222.9712.97642224.937
   717.8 2226.88   743.7 2227.75   761.7 2230.87   780.2 2228.56   882.8 2229.22
   916.1 2235.26   964.5 2232.56  1087.7 2233.53    1096 2236.37  1111.9 2252.51
  1120.6 2258.93  1161.7 2272.94  1215.1 2286.91  1239.7 2291.56  1338.6 2303.51
#Mann= 10 ,-1,0
       0     .07       0      20     .08       0     230     .07       0
     290     .06       0     640     .07       0682.7264    .045       0
712.9764     .07       0  856.92     .08       0  956.92     .07       0
 1156.92     .05       0
#XS Ineff= 2 , 0
                          728.65         2233.25
Permanent Ineff=
       F       F
Bank Sta=682.7264,712.9764
XS Rating Curve= 0 ,0
Exp/Cntr(USF)=0,0
Exp/Cntr=0.3,0.1

Type RM Length L Ch R = 1 ,423     ,104.7,108.4,112.5
BEGIN DESCRIPTION:
Structure 1 XS 4
END DESCRIPTION:
XS GIS Cut Line= 4
2339603.84447404696934.6449042692338975.00867716697126.738836457
2338859.02743508697344.2036653492339002.19178077697858.870427059
#Sta/Elev= 30
       0 2283.42    46.6 2274.58    70.8  2267.2     100 2263.41   120.9 2256.02
   158.6 2255.53   200.4    2252   539.2 2244.37   589.4 2241.28   618.7 2237.18
   657.5 2228.89   719.2  2228.9735.28492223.499   741.9 2222.12758.1149  2223.5
   769.1 2226.87   929.9 2226.75   996.3 2229.62  1012.9 2231.19  1029.6  2235.4
  1083.5 2231.99    1179 2233.39  1187.3 2237.23    1211  2259.8  1228.8 2266.27
  1256.5 2271.16  1277.6 2276.95  1328.5 2284.89  1405.9 2293.35  1438.2 2295.06
#Mann= 10 ,-1,0
       0     .06       0     100     .08       0     200     .07       0
     300     .06       0  697.52     .07       0735.2849    .045       0
758.1149     .07       0 1123.98     .08       0 1163.98     .07       0
 1223.98     .05       0
Bank Sta=735.2849,758.1149
XS Rating Curve= 0 ,0
Exp/Cntr(USF)=0,0
Exp/Cntr=0.3,0.1

Type RM Length L Ch R = 1 ,315     ,61.4,61.7,61.1
BEGIN DESCRIPTION:
Structure 1 XS 3
END DESCRIPTION:
XS GIS Cut Line= 6
2339495.96447921696786.5057386432339296.47855505696758.762663097
2339036.22208445697024.3035290362338869.76363117  697123.3859417
2338678.80458797697360.5682504472338901.12698154697893.469393314
#Sta/Elev= 30
       0 2276.96    40.2 2265.24   133.1 2245.52   177.5  2242.3   193.6 2238.31
   271.3 2237.72   480.6 2232.23   562.3 2232.11     648 2226.62   791.2 2224.98
   806.3 2221.39   820.4 2219.75   829.1 2219.93   835.72221.422   843.1 2224.44
   857.2 2225.42  1072.6 2223.61  1107.9 2224.19  1129.6 2223.03  1251.5 2225.57
  1272.9 2226.75  1302.9  2234.6  1346.3  2232.5  1359.3 2234.89  1393.9 2236.58
  1415.6  2240.7  1431.9 2247.73  1447.2 2249.48  1619.3 2292.43    1650 2298.92
#Mann= 14 ,-1,0
       0     .06       0      80     .07       0     160     .03       0
     180     .06       0  211.41     .07       0  321.41     .06       0
   806.3    .045       0   835.7     .07       0  956.88     .05       0
  986.88     .07       0 1066.88     .08       0 1182.56     .06       0
 1212.56     .07       0 1462.56     .05       0
Bank Sta=806.3,835.7
XS Rating Curve= 0 ,0
Exp/Cntr(USF)=0,0
Exp/Cntr=0.3,0.1

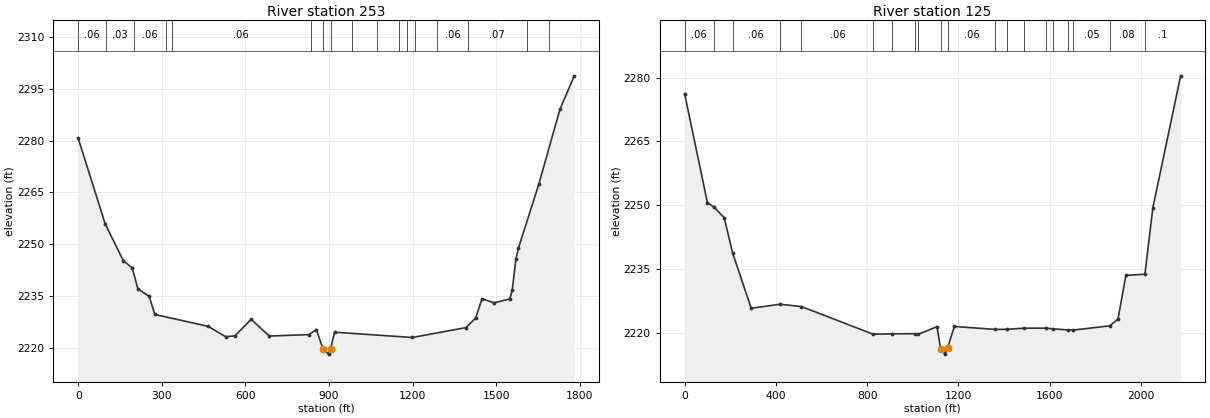
Type RM Length L Ch R = 1 ,253     ,132,128.7,126.4
BEGIN DESCRIPTION:
Structure 1 XS 2
END DESCRIPTION:
XS GIS Cut Line= 6
2339516.08110572696765.970121945 2339243.9347456 696726.33715688
  2338983.678275696991.8780228192338817.21982173697090.960435483
2338618.33418551697349.2803255982338864.43635812697908.603445176
#Sta/Elev= 30
       0 2280.68    96.9 2255.85   161.6 2245.22   193.9 2243.07   214.1 2237.01
   254.6 2234.82     275 2229.59   466.5 2226.13   529.2 2223.13   562.7  2223.4
   620.1 2228.18   685.4 2223.33   827.9 2223.75   854.5 2225.22   877.8 2219.61
   897.9 2218.08  905.282219.588   919.6 2224.44  1198.8 2222.91  1391.1 2225.78
    1426  2228.6  1448.8 2234.16  1491.6 2232.96  1548.4  2234.1  1557.1 2236.71
  1570.2 2245.61  1579.3 2248.86  1652.2 2267.33    1728 2289.07  1779.4 2298.83
#Mann= 17 ,-1,0
       0     .06       0     100     .03       0     200     .06       0
  315.02     .07       0  335.02     .06       0  833.98     .07       0
   877.8    .045       0  905.28     .07       0  980.67     .06       0
 1070.49     .07       0 1150.49      .1       0 1178.31     .06       0
 1208.31     .08       0 1288.31     .06       0 1398.31     .07       0
 1608.31      .1       0 1688.31     .05       0
Bank Sta=877.8,905.28
XS Rating Curve= 0 ,0
Exp/Cntr(USF)=0,0
Exp/Cntr=0.3,0.1

Type RM Length L Ch R = 1 ,125     ,,,
BEGIN DESCRIPTION:
Structure 1 XS 1
END DESCRIPTION:
XS GIS Cut Line= 4
2339518.07860848696716.9253269252338940.09836793696599.924914031
 2338417.3125034 697506.474118232338721.29971012697949.480772431
#Sta/Elev= 30
       0 2276.22    99.8  2250.6   128.5 2249.54   173.3 2247.06   210.1 2238.79
   291.7 2225.73   417.2 2226.67   512.1 2226.13   826.6 2219.61   909.7 2219.72
  1011.3 2219.75  1021.9 2219.56    1106  2221.41121.5892216.235  1140.6 2214.94
1152.2892216.438  1182.1 2221.44  1360.8 2220.76  1411.4 2220.77  1486.7 2221.04
  1582.4 2221.06  1615.6 2220.88  1678.3 2220.64  1702.5  2220.6  1862.6 2221.59
  1899.1 2223.18  1933.6 2233.46  2017.1 2233.74  2051.6 2249.31  2173.5 2280.41
#Mann= 20 ,-1,0
       0     .06       0   128.5     .03       0   210.1     .06       0
   417.2     .07       0   512.1     .06       0   826.6      .1       0
   909.7     .07       0  1011.3     .06       0  1021.9     .08       0
1121.589    .045       01152.289     .06       0  1360.8      .1       0
  1411.4     .06       0  1486.7      .1       0  1582.4     .08       0
  1615.6      .1       0  1678.3     .08       0  1702.5     .05       0
  1862.6     .08       0  2017.1      .1       0
Bank Sta=1121.589,1152.289
XS Rating Curve= 0 ,0
Exp/Cntr(USF)=0,0
Exp/Cntr=0.3,0.1
LCMann Table=0

Chan Stop Cuts=-1
Use User Specified Reach Order=0
Composite Channel Slope=5